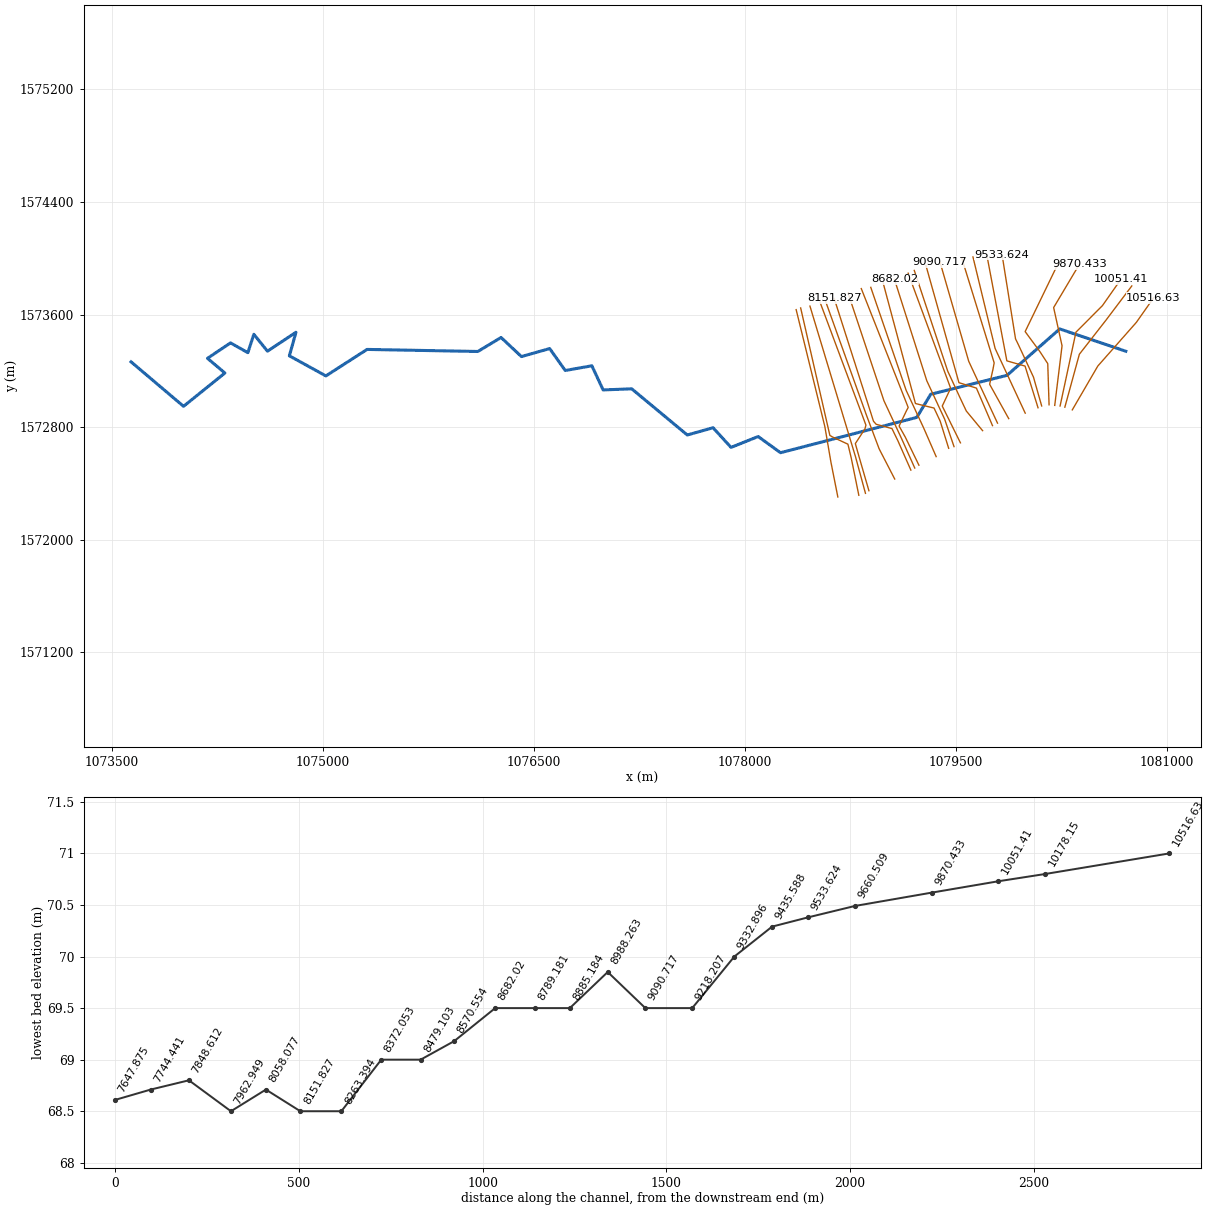
--- HECRAS_v2.prj (project) ---

Proj Title=HECRAS_v2
Current Plan=p03
Default Exp/Contr=0.3,0.1
SI Units
Geom File=g01
Geom File=g02
Flow File=f02
Flow File=f01
Unsteady File=u01
Unsteady File=u02
Plan File=p02
Plan File=p03
Plan File=p01
Plan File=p04
Y Axis Title=Elevation
X Axis Title(PF)=Main Channel Distance
X Axis Title(XS)=Station
BEGIN DESCRIPTION:
Modelo Hec Ras v2
Integracion del terreno natural con el cauce sinuoso disenado
Modelo creado a partir de HecGeoRAS
Elaboro: ECI
Fecha: 20161024
REVISION:
END DESCRIPTION:
DSS File=dss
DSS Export Rating Curves= 0
DSS Export Rating Curve Sorted= 0
DSS Export Volume Flow Curves= 0
DXF OffsetX= 0
DXF OffsetY= 0
DXF ScaleX= 1
DXF ScaleY= 10

--- HECRAS_v2.p03 (plan) ---

Plan Title=HECRAS_v2_NP2.33
Program Version=5.07
Short Identifier=HECRAS_v2_NP2.33
Simulation Date=05MAR2016,00:15,08MAR2016,00:15
Geom File=g01
Flow File=u01
Subcritical Flow
K Sum by GR= 0
Std Step Tol= 0.003
Critical Tol= 0.003
Num of Std Step Trials= 20
Max Error Tol= 0.1
Flow Tol Ratio= 0.001
Split Flow NTrial= 30
Split Flow Tol= 0.006
Split Flow Ratio= 0.02
Log Output Level= 0
Friction Slope Method= 1
Unsteady Friction Slope Method= 2
Unsteady Bridges Friction Slope Method= 1
Parabolic Critical Depth
Global Vel Dist= 0 , 0 , 0
Global Log Level= 0
CheckData=True
Encroach Param=-1 ,0,0, 0
Computation Interval=1MIN
Output Interval=15MIN
Instantaneous Interval=1HOUR
Mapping Interval=1HOUR
Computation Time Step Use Courant=        0
Computation Time Step Use Time Series=    0
Computation Time Step Count To Double=0
Computation Time Step Max Doubling=0
Computation Time Step Max Halving=0
Computation Time Step Residence Courant=0
Run HTab=-1
Run UNet=-1
Run Sediment= 0
Run PostProcess=-1
Run WQNet= 0
Run RASMapper=-1
UNET Theta= 1
UNET Theta Warmup= 1
UNET ZTol= 0.006
UNET ZSATol= 0.006
UNET MxIter= 20
UNET Max Iter WO Improvement= 0
UNET MaxInSteps= 0
UNET DtIC= 0
UNET DtMin= 0
UNET MaxCRTS= 20
UNET WFStab= 2
UNET SFStab= 1
UNET WFX= 1
UNET SFX= 1
UNET 1D Methodology=Finite Difference
UNET DSS MLevel= 4
UNET Pardiso=0
UNET DZMax Abort= 30
UNET Use Existing IB Tables=-1
UNET Froude Reduction=False
UNET Froude Limit= 0.8
UNET Froude Power= 4
UNET D1 Cores= 0
UNET D2 Coriolis=0
UNET D2 Cores= 0
UNET D2 Theta= 1
UNET D2 Theta Warmup= 1
UNET D2 Z Tol= 0.03
UNET D2 Volume Tol= 0.03
UNET D2 Max Iterations= 20
UNET D2 Equation= 0
UNET D2 RampUpFraction=0.1
UNET D2 TimeSlices= 1
UNET D2 BCVolumeCheck=0
UNET D1D2 MaxIter= 0
UNET D1D2 ZTol=0.03
UNET D1D2 QTol=0.1
UNET D1D2 MinQTol=0.03
DSS File=dss
Write IC File= 0
Write IC File at Fixed DateTime=0
Write IC File at Sim End=0
Echo Input=False
Echo Parameters=False
Echo Output=False
Write Detailed= 0
Computation Level Output=True
HDF Write Warmup=0
HDF Write Time Slices=0
HDF Flush=0
HDF Face Node Velocities=0
HDF Compression= 1
HDF Chunk Size= 1
HDF Spatial Parts= 1
HDF Use Max Rows=0
HDF Fixed Rows= 1
Calibration Method= 0
Calibration Iterations= 20
Calibration Max Change=0.05
Calibration Tolerance=0.2
Calibration Maximum=1.5
Calibration Minimum=0.5
Calibration Optimization Method= 1
WQ AD Non Conservative
WQ ULTIMATE=-1
WQ Max Comp Step=1HOUR
WQ Output Interval=15MIN
WQ Output Selected Increments= 0
WQ Output face flow=0
WQ Output face velocity=0
WQ Output face area=0
WQ Output face dispersion=0
WQ Output cell volume=0
WQ Output cell surface area=0
WQ Output cell continuity=0
WQ Output cumulative cell continuity=0
WQ Output face conc=0
WQ Output face dconc_dx=0
WQ Output face courant=0
WQ Output face peclet=0
WQ Output face adv mass=0
WQ Output face disp mass=0
WQ Output cell mass=0
WQ Output cell source sink temp=0
WQ Output nsm pathways=0
WQ Output nsm derived pathways=0
WQ Output MaxMinRange=-1
WQ Daily Max Min Mean=-1
WQ Daily Range=0
WQ Daily Time=0
WQ Create Restart=0
WQ Fixed Restart=0
WQ System Summary=0
WQ Write To DSS=0
WQ Use Fixed Temperature=0
Sorting and Armoring Iterations= 10
XS Update Threshold= 0.02
Bed Roughness Predictor= 0
Hydraulics Update Threshold= 0.02
Energy Slope Method= 1
Volume Change Method= 1
Sediment Retention Method= 0
XS Weighting Method= 0
Number of US Weighted Cross Sections= 1
Number of DS Weighted Cross Sections= 1
Upstream XS Weight=0
Main XS Weight=1
Downstream XS Weight=0
Number of DS XS's Weighted with US Boundary= 1
Upstream Boundary Weight= 1
Weight of XSs Associated with US Boundary= 0
Number of US XS's Weighted with DS Boundary= 1
Downstream Boundary Weight= 0.5
Weight of XSs Associated with DS Boundary= 0.5
Percentile Method= 0
Sediment Output Level= 4
Mass or Volume Output= 0
Output Increment Type= 1
Profile and TS Output Increment= 1
XS Output Flag= 0
XS Output Increment= 10
Write Gradation File= 0
Read Gradation Hotstart= 0
Write HDF5 File= 1
Write Binary Output= 1
Write DSS Sediment File= 0
SV Curve= 0
Specific Gage Flag= 0

--- HECRAS_v2.p01 (plan) ---

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Plan Title=HECRAS_v2_NP100
Program Version=5.03
Short Identifier=HECRAS_v2_NP100
Geom File=g02
Flow File=u02
Run HTab= 1
Run UNet= 1
Run PostProcess= 1
Run RASMapper= 1
UNET Time Slicing=0,0, 5
UNET D2 Z Tol= 0.003
UNET D2 Volume Tol= 0.003
UNET D1D2 ZTol=0.003

--- HECRAS_v2.p02 (plan) ---

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Plan Title=HECRAS_v2_Permanente
Short Identifier=HECRAS_v2_Pe
Geom File=g01
Flow File=f02
Calc Critical at every XS
Output Interval=1HOUR
Run HTab= 0
Run UNet= 0
Run PostProcess= 0
Run RASMapper= 0
UNET D2 Z Tol= 0.003
UNET D2 Volume Tol= 0.003
UNET D1D2 ZTol=0.003

--- HECRAS_v2.p04 (plan) ---

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Plan Title=HECRAS_v2_PermanenteA
Program Version=5.03
Short Identifier=HECRAS_v2_PermanenteA
Geom File=g01
Flow File=f01
Output Interval=1HOUR
Run HTab= 0
Run UNet= 0
Run PostProcess= 0
Run RASMapper= 0
UNET Time Slicing=0,0, 5
UNET D2 Z Tol= 0.003
UNET D2 Volume Tol= 0.003
UNET D1D2 ZTol=0.003

--- HECRAS_v2.f01 (steady flow) ---

Flow Title=HECRAS_v2_PermanenteA
Program Version=5.03
Number of Profiles= 1
Profile Names=Tr=2.33yr
River Rch & RM=ARROYOELZORRO,ARRIBALAT1      ,10516.63
     130
River Rch & RM=ARROYOELZORRO,ARRIBALAT1      ,8885.184
   129.6
River Rch & RM=ARROYOELZORRO,ABAJOLAT1       ,8885.184
   129.6
River Rch & RM=LATERAL1,LATERAL1        ,4571.366
      42
Boundary for River Rch & Prof#=ARROYOELZORRO,ARRIBALAT1      , 1
Up Type= 2
Dn Type= 3
Dn Slope=0.0008969
Boundary for River Rch & Prof#=ARROYOELZORRO,ABAJOLAT1       , 1
Up Type= 0
Dn Type= 3
Dn Slope=0.0008969
Boundary for River Rch & Prof#=LATERAL1,LATERAL1        , 1
Up Type= 2
Dn Type= 0
DSS Import GetInterval= 0
DSS Import GetPeak= 0
DSS Import FillOption= 0

--- HECRAS_v2.f02 (steady flow) ---

Flow Title=HECRAS_v2_Permanente
Program Version=5.07
Number of Profiles= 2
Profile Names=Tr=2.33yr,Tr=100yr
River Rch & RM=ARROYOELZORRO,ARRIBALAT1      ,10516.63
     130   522.1
Boundary for River Rch & Prof#=ARROYOELZORRO,ARRIBALAT1      , 1
Up Type= 2
Dn Type= 3
Dn Slope=0.0008969
Boundary for River Rch & Prof#=ARROYOELZORRO,ARRIBALAT1      , 2
Up Type= 2
Dn Type= 3
Dn Slope=0.0008969
Boundary for River Rch & Prof#=ARROYOELZORRO,ABAJOLAT1       , 1
Up Type= 0
Dn Type= 3
Dn Slope=0.0008969
Boundary for River Rch & Prof#=ARROYOELZORRO,ABAJOLAT1       , 2
Up Type= 0
Dn Type= 3
Dn Slope=0.0008969
Boundary for River Rch & Prof#=LATERAL1,LATERAL1        , 1
Up Type= 2
Dn Type= 0
Boundary for River Rch & Prof#=LATERAL1,LATERAL1        , 2
Up Type= 2
Dn Type= 0
DSS Import GetInterval= 0
DSS Import GetPeak= 0
DSS Import FillOption= 0

--- HECRAS_v2.u01 (unsteady flow) ---

Flow Title=Tr2.33yrNoPermanente
Program Version=5.07
Use Restart= 0
Initial Flow Loc=ARROYOELZORRO   ,ARRIBALAT1      ,10516.63,0.001
Boundary Location=ARROYOELZORRO   ,ARRIBALAT1      ,10516.63,        ,                ,                ,                ,
Interval=1MIN
Flow Hydrograph= 4321
       0       0       0       0       0       0       0       0       0       0
       0       0       0       0       0       0       0       0       0       0
       0       0       0       0       0       0       0       0       0       0
       0       0       0       0       0       0       0       0       0       0
       0       0       0       0       0       0      .1      .1      .1      .1
      .1      .1      .1      .1      .1      .1      .2      .2      .2      .2
      .2      .2      .3      .3      .3      .3      .4      .4      .4      .4
      .5      .5      .5      .6      .6      .6      .7      .7      .7      .8
      .8      .9      .9       1       1     1.1     1.1     1.2     1.2     1.3
     1.4     1.4     1.5     1.6     1.6     1.7     1.8     1.8     1.9       2
     2.1     2.1     2.2     2.3     2.4     2.5     2.6     2.7     2.7     2.8
     2.9       3     3.1     3.2     3.3     3.4     3.5     3.6     3.8     3.9
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Use DSS=False
Use Fixed Start Time=True
Fixed Start Date/Time=05MAR2016,00:15
Is Critical Boundary=False
Boundary Location=ARROYOELZORRO   ,ARRIBALAT1      ,200     ,        ,                ,                ,                ,
Friction Slope=0.000897,0

--- HECRAS_v2.u02 (unsteady flow) ---

Flow Title=Tr100yrNoPermanente
Program Version=5.03
Use Restart= 0
Boundary Location=ARROYOELZORRO   ,ARRIBALAT1      ,10516.63,        ,                ,                ,                ,
Interval=1MIN
Flow Hydrograph= 4321
       0       0       0       0       0       0       0       0       0       0
       0       0       0       0       0       0       0       0       0       0
       0       0       0       0      .1      .1      .1      .1      .1      .1
      .1      .2      .2      .2      .3      .3      .3      .4      .4      .5
      .5      .6      .6      .7      .7      .8      .9       1     1.1     1.1
     1.2     1.3     1.4     1.5     1.7     1.8     1.9       2     2.2     2.3
     2.5     2.6     2.8     2.9     3.1     3.3     3.5     3.7     3.9     4.1
     4.3     4.5     4.7       5     5.2     5.4     5.7       6     6.2     6.5
     6.8     7.1     7.4     7.7       8     8.3     8.6     8.9     9.2     9.6
     9.9    10.3    10.6      11    11.4    11.7    12.1    12.5    12.9    13.3
    13.7    14.1    14.5    14.9    15.3    15.8    16.2    16.7    17.1    17.6
      18    18.5    18.9    19.4    19.9    20.4    20.9    21.4    21.8    22.4
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Use DSS=False
Use Fixed Start Time=True
Fixed Start Date/Time=05MAR2016,00:15
Is Critical Boundary=False
Boundary Location=LATERAL1        ,LATERAL1        ,4571.366,        ,                ,                ,                ,
Interval=1MIN
Flow Hydrograph= 4321
       0       0       0       0       0       0       0       0       0       0
       0       0       0       0       0       0       0       0      .1      .1
      .1      .1      .1      .1      .2      .2      .2      .2      .3      .3
      .3      .4      .4      .5      .5      .6      .6      .7      .8      .8
      .9       1     1.1     1.2     1.2     1.3     1.4     1.5     1.7     1.8
     1.9       2     2.1     2.3     2.4     2.6     2.7     2.9       3     3.2
     3.4     3.5     3.7     3.9     4.1     4.3     4.5     4.7     4.9     5.1
     5.4     5.6     5.8     6.1     6.3     6.6     6.8     7.1     7.3     7.6
     7.9     8.2     8.5     8.8     9.1     9.4     9.7    10.1    10.4    10.7
    11.1    11.5    11.8    12.2    12.6      13    13.3    13.7    14.2    14.6
      15    15.4    15.9    16.3    16.8    17.2    17.7    18.2    18.7    19.2
    19.7    20.2    20.7    21.2    21.8    22.3    22.9    23.5      24    24.6
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Use DSS=False
Use Fixed Start Time=True
Fixed Start Date/Time=05MAR2016,00:15
Is Critical Boundary=False
Boundary Location=ARROYOELZORRO   ,ARRIBALAT1      ,3253.451,        ,                ,                ,                ,
Friction Slope=0.0008969

--- HECRAS_v2.g01 (geometry) ---

Geom Title=HECRAS_v2
Program Version=5.07

River Reach=ARROYOELZORRO   ,ARRIBALAT1
Reach XY= 30
 1080707.43739681573339.58328046 1080237.79819681573498.13468046
 1079862.93129681573168.18948046 1079320.61779681573033.81938046
 1079221.68659681572869.42468046 1078253.10579681572618.30508046
 1078094.25239681572733.38278046 1077901.52499681572656.19918046
 1077773.54629681572795.83678046 1077590.45549681572744.39078046
 1077195.64859681573072.34628046 1076992.29679681573064.68888046
 1076912.25779681573236.15908046 1076722.99529681573202.64758046
 1076612.41459681573358.39158046 1076411.53539681573301.74318046
 1076266.83699681573437.28828046 1076101.90009681573337.85438046
 1075314.21129681573352.51228046 1075021.83569681573164.16158046
 1074762.10359681573307.02038046 1074809.06719681573474.36958046
 1074606.39599681573339.96098046 1074509.69059681573460.08208046
 1074467.14769681573329.44928046 1074343.85159681573398.90258046
 1074180.20649681573289.10028046 1074303.89949681573184.85428046
 1074009.94679681572948.05168046 1073636.69609681573264.44158046

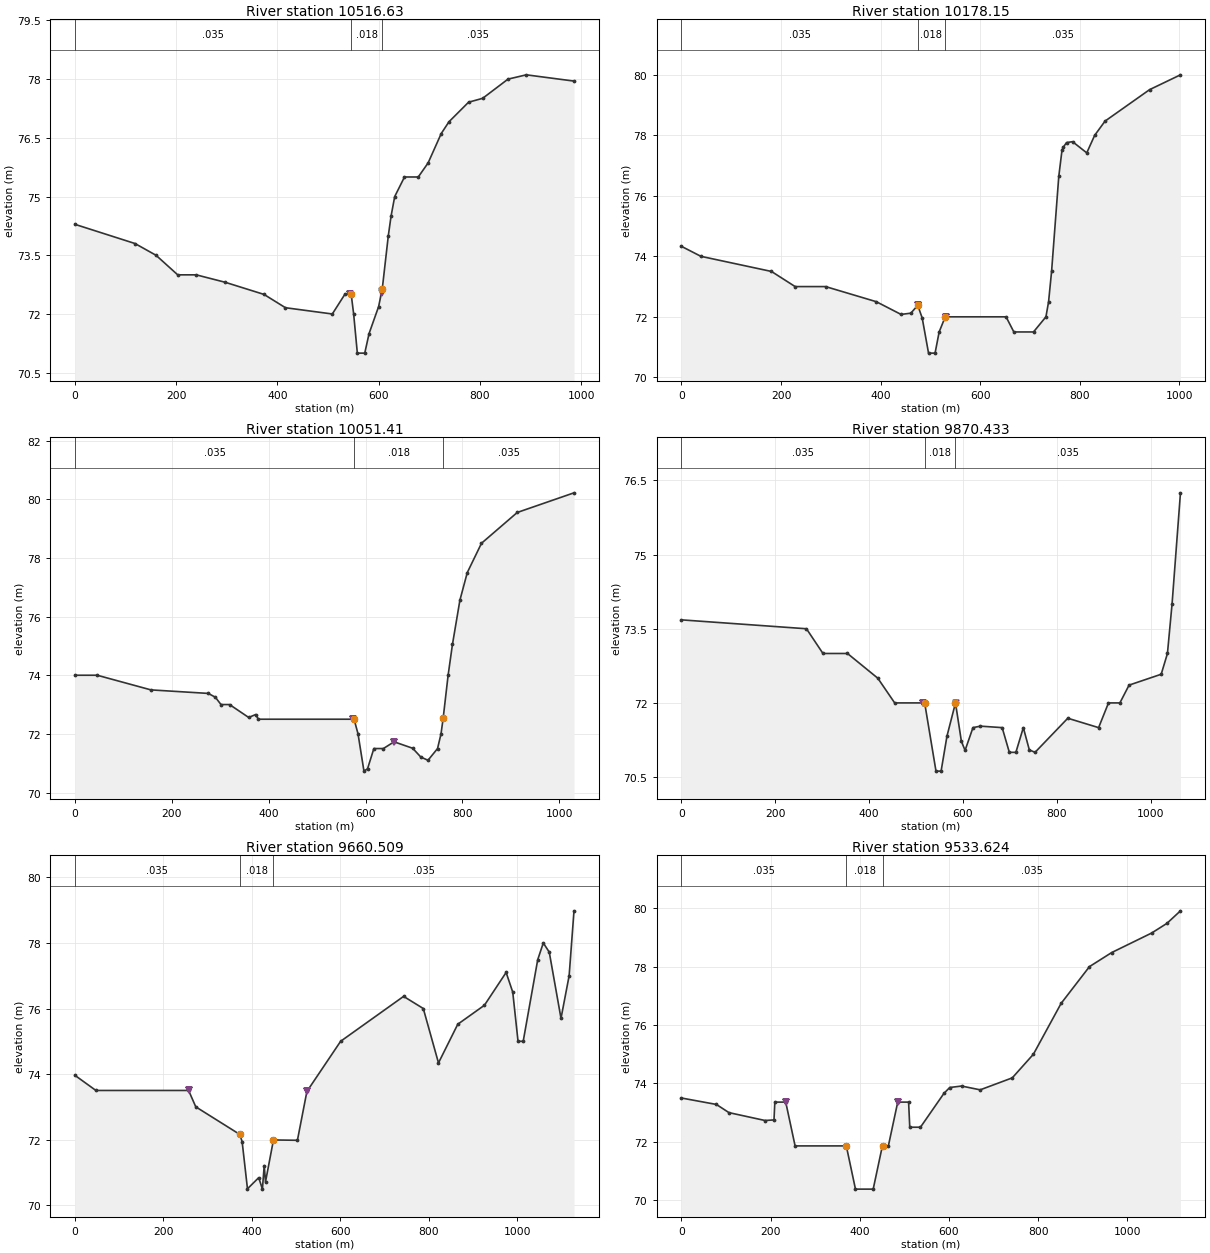
Type RM Length L Ch R = 1 ,10516.63,326.71,338.48,272.19
BEGIN DESCRIPTION:
Natural inicio
END DESCRIPTION:
XS GIS Cut Line= 4
    1080327.0311    1572922.9204    1080508.3292    1573234.2431
    1080782.3396     1573544.788    1080904.0514    1573717.6348
#Sta/Elev= 30
       0   74.29  118.58    73.8  160.09    73.5  202.95      73  239.59      73
  296.77   72.81  373.39    72.5  415.77   72.16  508.37      72  533.01    72.5
  545.68    72.5   550.5      72  557.78      71  572.44      71  580.98    71.5
  599.85   72.19  607.03   72.64  618.98      74  624.41    74.5  631.62      75
  650.95    75.5  678.17    75.5  697.65   75.86  723.54   76.61  738.77   76.91
  777.51   77.41  805.43   77.51   855.4      78   891.6   78.11  985.81   77.95
#Mann= 3 , 0 , 0
       0    .035       0  545.68    .018       0  607.03    .035       0
Levee=-1,544.02,72.5,-1,606.21,72.54,,
Bank Sta=545.68,607.03
XS Rating Curve= 0 ,0
Pilot Channel=71,60,0.018
Exp/Cntr=0.3,0.1

Type RM Length L Ch R = 1 ,10178.15,130.71,126.74,122.71
BEGIN DESCRIPTION:
Natural inicio
END DESCRIPTION:
XS GIS Cut Line= 4
    1080274.1143    1572941.9705    1080377.2263    1573318.1105
    1080566.5631    1573560.6676    1080749.9587    1573803.7037
#Sta/Elev= 30
       0   74.33   39.05      74  180.78    73.5  228.31      73  289.46      73
  391.35    72.5  440.96   72.08  460.63   72.12  474.55   72.38  483.53   71.96
  496.23    70.8  509.34    70.8  517.56    71.5  529.76      72  651.94      72
  667.53    71.5  707.05    71.5  732.02      72  737.33    72.5  743.35    73.5
  757.79   76.64  764.21    77.5   766.6    77.6  773.33   77.76  785.48   77.79
     814   77.42  829.89      78  850.74   78.47  940.18   79.51 1002.19      80
#Mann= 3 , 0 , 0
       0    .035       0  474.55    .018       0  529.76    .035       0
Levee=-1,474.29,72.38,-1,531.73,72,,
Bank Sta=474.55,529.76
XS Rating Curve= 0 ,0
Pilot Channel=70.798,60,0.018
Exp/Cntr=0.3,0.1

Type RM Length L Ch R = 1 ,10051.41,150.51,180.98,211.46
BEGIN DESCRIPTION:
Natural inicio
END DESCRIPTION:
XS GIS Cut Line= 4
    1080240.2476    1572950.4372    1080352.9475    1573475.0008
     1080541.224    1573663.8071    1080671.8044    1573849.7252
#Sta/Elev= 30
       0      74   45.82      74  156.83    73.5  275.24   73.38   289.8   73.25
  301.48      73  319.19      73  358.67   72.56  373.11   72.66  378.61    72.5
  576.26    72.5  584.43      72  596.67   70.73  604.06   70.81  617.13    71.5
  636.79    71.5  658.87   71.73  697.24   71.51  714.07   71.21  728.91    71.1
  748.62    71.5  755.78      72  760.27   72.54  770.45      74  779.39   75.05
   794.8   76.56     810    77.5  839.36    78.5  913.18   79.55 1030.37   80.22
#Mann= 3 , 0 , 0
       0    .035       0  576.26    .018       0  760.27    .035       0
Levee=-1,573.84,72.5,-1,658.76,71.73,,
Bank Sta=576.26,760.27
XS Rating Curve= 0 ,0
Pilot Channel=70.723,60,0.018
Exp/Cntr=0.3,0.1

Type RM Length L Ch R = 1 ,9870.433,205.56,209.92,222.26
BEGIN DESCRIPTION:
Natural inicio
END DESCRIPTION:
XS GIS Cut Line= 4
    1080202.1475    1572954.6705    1080254.1813     1573378.091
    1080194.4311    1573650.0588     1080377.746    1573958.0837
#Sta/Elev= 30
       0   73.68  266.43    73.5  301.61      73  353.82      73  418.46    72.5
  454.44      72  518.34      72  542.47   70.62  553.36   70.62  565.92   71.33
  584.02      72  596.64   71.22  604.48   71.04  621.28    71.5  637.17   71.53
   683.5    71.5  698.79      71  712.74      71  728.62    71.5  741.37   71.05
  753.58      71  823.39   71.69  889.07    71.5  910.13      72   934.4      72
  953.99   72.36 1022.46   72.58 1035.75      73 1045.59      74 1063.51   76.25
#Mann= 3 , 0 , 0
       0    .035       0  518.34    .018       0  584.02    .035       0
Levee=-1,515.08,71.99,-1,584.68,71.99,,
Bank Sta=518.34,584.02
XS Rating Curve= 0 ,0
Pilot Channel=70.615,60,0.018
Exp/Cntr=0.3,0.1

Type RM Length L Ch R = 1 ,9660.509,133.24,126.88,116.59
BEGIN DESCRIPTION:
Natural inicio
END DESCRIPTION:
XS GIS Cut Line= 5
    1080161.9306    1572958.9446    1080152.5873    1573251.4818
    1080095.9811    1573338.1023    1079991.8435    1573479.1967
    1080234.5059    1573980.1218
#Sta/Elev= 30
       0   73.96   47.29    73.5  256.84    73.5  273.09      73  372.39   72.16
  377.86   71.94  389.93    70.5  415.39   70.84   423.7   70.49  427.79   71.21
  430.69   70.71  448.67   71.99  502.86   71.98  524.29   73.47  600.56      75
   742.9   76.37  787.41      76  821.77   74.34  865.37   75.52  925.67    76.1
  974.68    77.1  989.65    76.5 1001.61      75 1013.29      75 1046.13   77.49
 1058.71      78  1072.2   77.72 1098.75    75.7 1117.14      77 1128.13   78.98
#Mann= 3 , 0 , 0
       0    .035       0  372.39    .018       0  448.67    .035       0
Levee=-1,256.84,73.5,-1,524.29,73.47035,,	451
Bank Sta=372.39,448.67
XS Rating Curve= 0 ,0
Pilot Channel=70.49,60,0.018
Exp/Cntr=0.3,0.1

Type RM Length L Ch R = 1 ,9533.624,62.94,98.04,133.14
XS GIS Cut Line= 5
    1080109.3166     1572950.726    1080050.9978    1573155.8972
     1079943.577     1573386.726    1079923.5675    1573427.4895
    1079827.7994    1574025.7831
#Sta/Elev= 30
       0    73.5   78.34   73.28   106.5      73  187.46   72.73  207.56   72.75
  209.43   73.36  233.88   73.36  254.88   71.86  369.71   71.86  390.29   70.38
  430.04   70.38  450.66   71.86  451.65   71.86  464.08   71.86  485.08   73.36
  509.48   73.36  512.06    72.5  536.06    72.5  588.78   73.66  601.72   73.86
  628.31   73.91  669.99   73.78  741.98   74.19  789.41      75  851.53   76.74
  915.15      78  964.85   78.48 1054.62   79.15 1088.83   79.48 1119.22   79.91
#Mann= 3 , 0 , 0
       0    .035       0  369.71    .018       0  451.65    .035       0
Levee=-1,233.88,73.36314,-1,485.08,73.36273,	452,	451
Bank Sta=369.71,451.65
XS Rating Curve= 0 ,0
Exp/Cntr=0.3,0.1

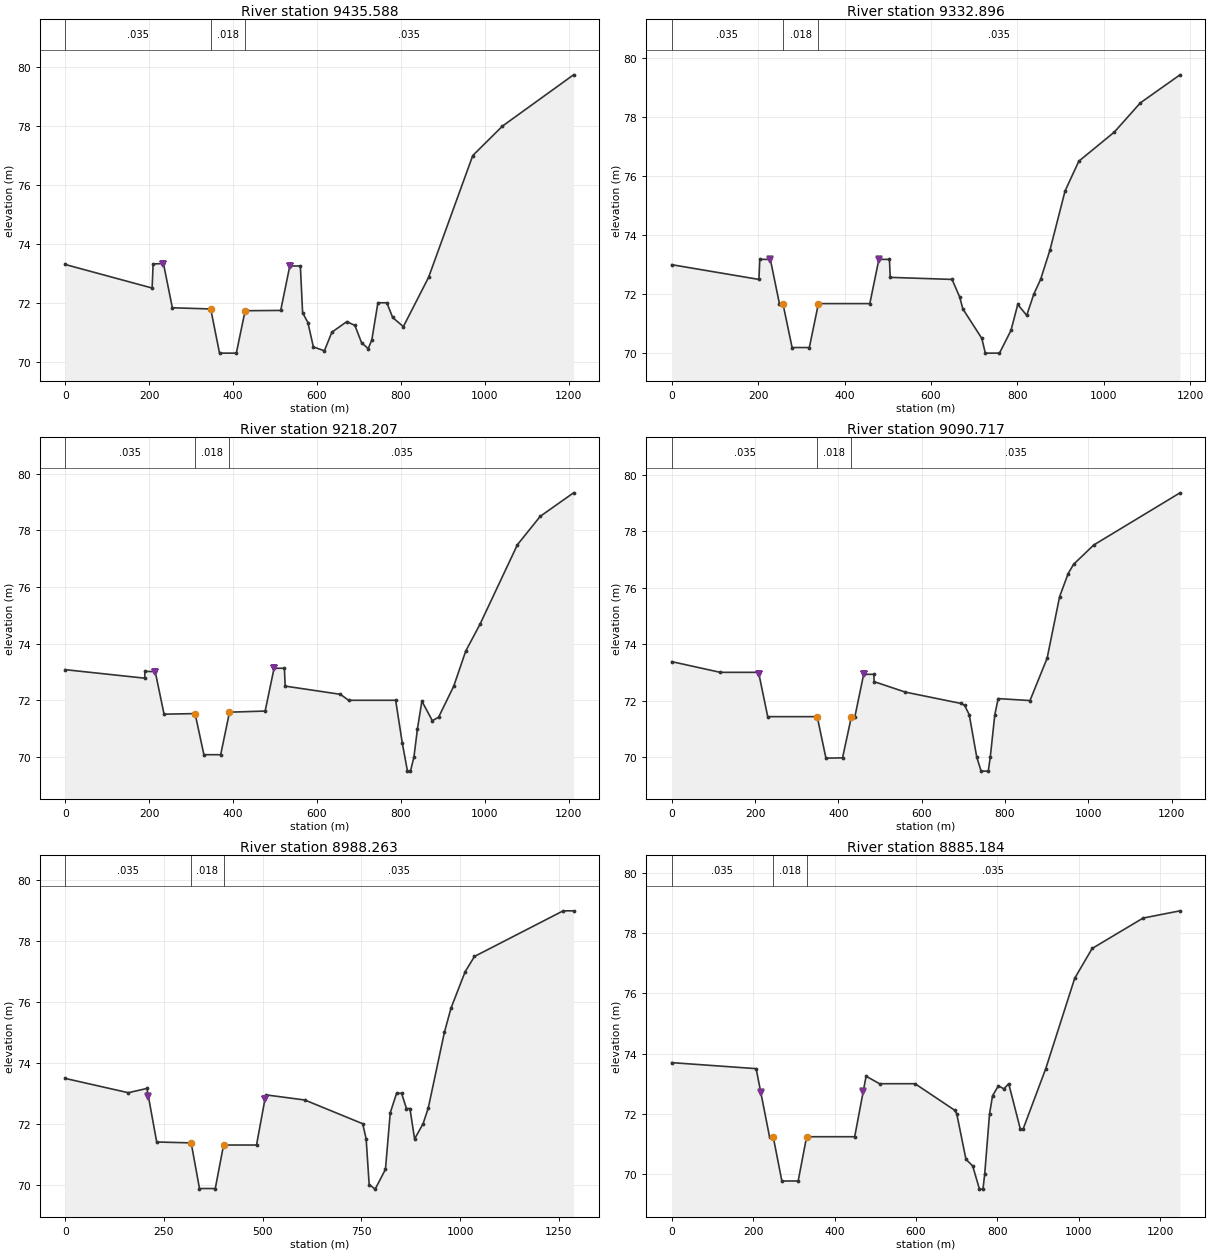
Type RM Length L Ch R = 1 ,9435.588,137.8,102.69,67.58
XS GIS Cut Line= 4
    1080083.4932    1572937.8142    1079991.2064    1573234.1482
     1079861.851     1573271.218    1079719.4258    1574024.0897
#Sta/Elev= 30
       0    73.3  207.07    72.5  209.48   73.32   234.1   73.33  255.29   71.83
   346.7   71.79   367.7   70.29   407.7   70.29   428.7   71.73  513.46   71.74
  535.12   73.25   560.3   73.25  565.65   71.66  578.22   71.33   591.3    70.5
   617.6   70.37  635.33      71  670.92   71.36  690.23   71.23  705.96   70.65
  721.87   70.44  730.54   70.74  745.07      72   766.4      72  780.24    71.5
  805.68   71.19  865.68   72.86  971.08      77 1041.89      78 1211.16   79.74
#Mann= 3 , 0 , 0
       0    .035       0   346.7    .018       0   428.7    .035       0
Levee=-1,234.1,73.32671,-1,535.13,73.24612,	452,	451
Bank Sta=346.7,428.7
XS Rating Curve= 0 ,0
Exp/Cntr=0.3,0.1

Type RM Length L Ch R = 1 ,9332.896,141.46,114.69,87.92
XS GIS Cut Line= 3
    1079992.4764    1572899.5025    1079778.3077     1573359.714
    1079621.0007    1574009.6964
#Sta/Elev= 30
       0      73  201.91    72.5  203.94   73.18  228.34   73.18  249.34   71.68
  257.43   71.68  278.72   70.19  318.56   70.19  339.62   71.68  458.54   71.68
  479.54   73.18  503.94   73.18  505.77   72.57  648.86    72.5  666.35   71.91
  673.85    71.5  717.72    70.5  725.81      70  758.58      70   785.2   70.77
  800.92   71.65  821.59   71.28  838.01      72  853.74    72.5  875.49    73.5
  910.34    75.5  942.17   76.51  1024.5    77.5 1084.68   78.49 1176.35   79.44
#Mann= 3 , 0 , 0
       0    .035       0  257.43    .018       0  339.62    .035       0
Levee=-1,228.34,73.17561,-1,479.54,73.17561,	452,	451
Bank Sta=257.43,339.62
XS Rating Curve= 0 ,0
Exp/Cntr=0.3,0.1

Type RM Length L Ch R = 1 ,9218.207,100.72,127.49,154.26
XS GIS Cut Line= 5
    1079875.0012    1572860.7674    1079739.5342    1573104.6079
    1079763.8079    1573214.4359    1079771.7076    1573257.0082
    1079542.2605    1573998.6897
#Sta/Elev= 30
       0   73.08  189.26   72.78  189.98   73.02  214.44   73.01   235.5   71.51
  309.42   71.53  330.42   70.08  370.42   70.08  391.42   71.58  476.37   71.62
  497.57   73.13  522.19   73.13  524.11    72.5  655.81   72.21  674.96      72
  787.28      72  802.99    70.5  815.42    69.5   822.6    69.5  830.88      70
  839.26      71  849.81   71.97  874.64   71.28  889.48    71.4  925.71    72.5
  954.33   73.74  988.14   74.68 1077.42   77.49 1131.71   78.49 1211.08   79.32
#Mann= 3 , 0 , 0
       0    .035       0  309.42    .018       0  391.42    .035       0
Levee=-1,214.44,73.01493,-1,497.56,73.12814,	452,	451
Bank Sta=309.42,391.42
XS Rating Curve= 0 ,0
Exp/Cntr=0.3,0.1

Type RM Length L Ch R = 1 ,9090.717,68.21,102.45,136.69
XS GIS Cut Line= 3
    1079795.4143     1572828.594    1079590.7473    1573268.3881
    1079386.4735    1573974.1363
#Sta/Elev= 30
       0   73.38  116.52      73  206.87      73  208.66   72.99  230.48   71.43
  349.22   71.43  370.18   69.96  410.01   69.97  431.31   71.43  439.68   71.43
  460.68   72.93  485.08   72.93   485.9   72.67  560.63    72.3  693.61    71.9
  702.99   71.83  714.03    71.5  732.03      70  742.52    69.5  759.73    69.5
  764.57      70  775.42    71.5  783.49   72.07  859.84      72  900.92    73.5
  930.92   75.68   951.4    76.5  964.59   76.83 1012.64   77.51  1219.8   79.36
#Mann= 3 , 0 , 0
       0    .035       0  349.22    .018       0  431.31    .035       0
Levee=-1,209.48,72.93304,-1,460.68,72.93301,	452,	451
Bank Sta=349.22,431.31
XS Rating Curve= 0 ,0
Exp/Cntr=0.3,0.1

Type RM Length L Ch R = 1 ,8988.263,137.11,103.08,68.73
XS GIS Cut Line= 4
    1079759.8543     1572810.814     1079645.554    1573077.6204
    1079521.3471    1573116.0751    1079286.2491    1573950.7471
#Sta/Elev= 30
       0   73.49  159.73   73.02  207.05   73.16  231.71    71.4  319.07   71.37
  340.07   69.87  380.07   69.87  401.07    71.3  484.52    71.3  507.93   72.95
  606.87   72.78   753.5      72  762.21    71.5  769.83      70  785.04   69.85
  811.06    70.5  823.24   72.36   839.2      73   852.1      73  864.25    72.5
   873.1    72.5  884.88    71.5  906.36      72  919.57   72.52  960.28      75
  977.07    75.8 1012.99      77 1036.56    77.5 1261.22      79 1287.43      79
#Mann= 3 , 0 , 0
       0    .035       0  319.07    .018       0  401.07    .035       0
Levee=-1,210.7,72.89437,-1,505.8,72.80102,	452,	451
Bank Sta=319.07,401.07
XS Rating Curve= 0 ,0
Exp/Cntr=0.3,0.1

Type RM Length L Ch R = 1 ,8885.184,132.08,96,60.24
XS GIS Cut Line= 5
    1079689.4749    1572775.0158    1079573.3755    1572915.1394
    1079527.1627    1573013.1873     1079441.341    1573198.8588
    1079203.8048    1573913.9964
#Sta/Elev= 30
       0    73.7  207.42    73.5  240.31   71.24  249.34   71.24  270.65   69.77
  310.66   69.77  331.47   71.24  449.51   71.24  477.54   73.25  510.44      73
  597.78      73     695   72.12  700.19      72  722.78   70.49  739.33   70.27
  755.91    69.5  764.56    69.5  768.83      70  780.68      72  788.11    72.6
  802.42   72.93  815.94   72.83  827.78      73  856.22    71.5  863.31    71.5
  918.75    73.5  989.86    76.5 1032.67   77.49 1157.89    78.5 1248.47   78.74
#Mann= 3 , 0 , 0
       0    .035       0  249.34    .018       0  331.47    .035       0
Levee=-1,219.31,72.74111,-1,470.51,72.74126,	452,	451
Bank Sta=249.34,331.47
XS Rating Curve= 0 ,0
Exp/Cntr=0.3,0.1

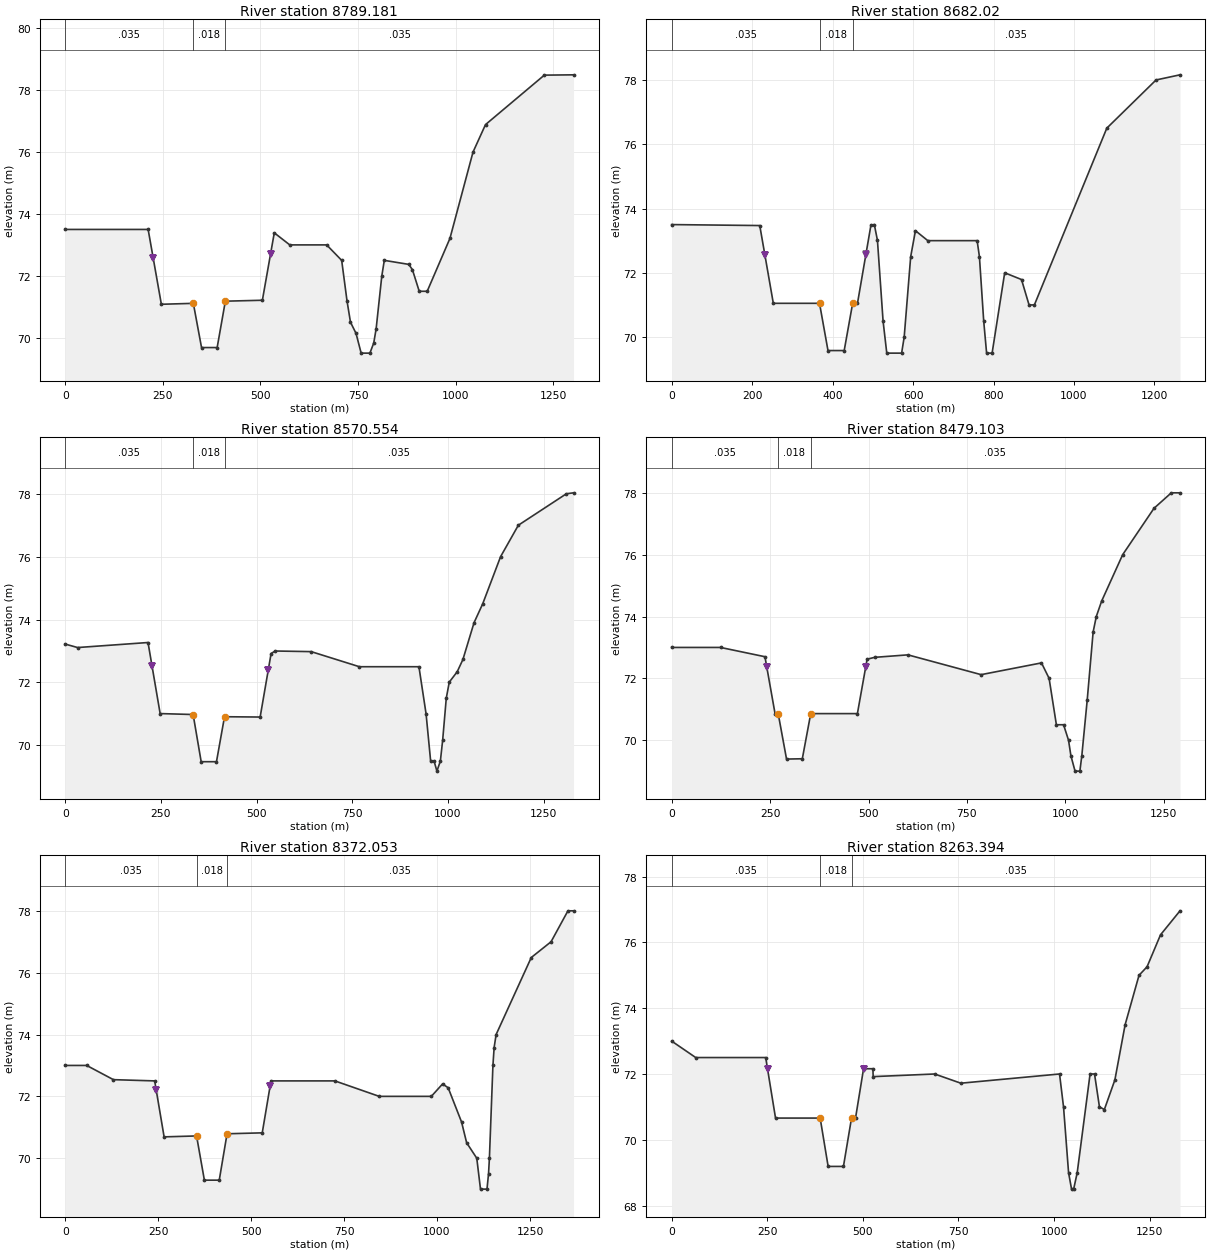
Type RM Length L Ch R = 1 ,8789.181,71.26,107.16,143.04
XS GIS Cut Line= 5
    1079531.8761    1572688.6196    1079402.7592    1572950.0285
    1079453.2203    1573057.3448    1079460.9676    1573080.2037
    1079160.4004    1573894.0637
#Sta/Elev= 30
       0    73.5   212.4    73.5  246.26   71.08  328.15   71.11  349.15   69.68
  389.15   69.68  410.15   71.18  504.98   71.21  535.47   73.39  575.11      73
  669.62      73  708.06    72.5  721.73   71.19  730.62    70.5  744.79   70.14
  757.94    69.5  780.38    69.5  790.23   69.83  796.36   70.29  810.78   71.99
  817.23    72.5  879.82   72.37  889.21    72.2  906.69    71.5  927.07    71.5
  985.34   73.21 1044.39      76 1076.42   76.89 1227.07   78.49 1301.87    78.5
#Mann= 3 , 0 , 0
       0    .035       0  328.15    .018       0  410.15    .035       0
Levee=-1,225.26,72.58036,-1,526.05,72.71256,	452,	451
Bank Sta=328.15,410.15
XS Rating Curve= 0 ,0
Exp/Cntr=0.3,0.1

Type RM Length L Ch R = 1 ,8682.02 ,74.63,111.47,148.33
XS GIS Cut Line= 4
    1079486.3677    1572661.6321    1079419.3723    1572857.7406
    1079292.7963    1573129.7306    1079063.1393    1573850.2486
#Sta/Elev= 30
       0    73.5  218.95   73.47  252.64   71.05  367.49   71.05  388.54   69.58
  428.82   69.58  449.82   71.05  461.84   71.05  495.23   73.48  503.71    73.5
  511.46   73.01  525.43    70.5  534.64    69.5  571.54    69.5  577.94      70
  594.06    72.5   605.9   73.31  636.65      73  759.24      73  764.93    72.5
  775.55    70.5  782.78    69.5  796.46    69.5  827.74      72  869.52   71.79
  888.28      71  901.54      71 1081.53    76.5 1203.96      78 1263.47   78.16
#Mann= 3 , 0 , 0
       0    .035       0  367.49    .018       0  449.82    .035       0
Levee=-1,231.64,72.55075,-1,482.84,72.55075,	452,	451
Bank Sta=367.49,449.82
XS Rating Curve= 0 ,0
Exp/Cntr=0.3,0.1

Type RM Length L Ch R = 1 ,8570.554,128.33,91.45,54.52
XS GIS Cut Line= 6
    1079448.3734    1572649.6729    1079387.8709    1572843.0808
    1079344.2332    1572935.8468    1079236.2393    1572961.8225
     1079212.153    1572968.0202    1078982.7058    1573824.8486
#Sta/Elev= 30
       0   73.22   32.43   73.11  216.39   73.27  248.05   71.01  334.24   70.98
  355.24   69.48  395.24   69.48  416.24   70.91  509.33    70.9  537.96   72.92
  548.72      73  642.69   72.98  768.63    72.5  924.21    72.5  942.88      71
  954.78    69.5  963.72    69.5   971.2   69.18  980.22    69.5  986.24   70.17
  995.65    71.5 1003.46   72.01 1024.17   72.34 1039.11   72.73 1068.18    73.9
 1090.81    74.5 1137.54      76 1183.97      77 1309.43      78 1328.13   78.03
#Mann= 3 , 0 , 0
       0    .035       0  334.24    .018       0  416.24    .035       0
Levee=-1,227.05,72.51025,-1,530.65,72.40443,	452,	451
Bank Sta=334.24,416.24
XS Rating Curve= 0 ,0
Exp/Cntr=0.3,0.1

Type RM Length L Ch R = 1 ,8479.103,143.28,107.05,70.86
XS GIS Cut Line= 4
    1079359.4733    1572590.4061    1079272.7216    1572789.4938
    1079146.1456    1573061.4837    1078894.6523    1573793.5218
#Sta/Elev= 30
       0      73  124.03      73  236.91    72.7  262.57   70.86  270.55   70.86
  291.77   69.39  331.85    69.4  353.22   70.86  471.77   70.86  496.41   72.62
  515.77   72.68  600.11   72.76  786.04   72.12  939.38    72.5  958.72      72
  977.18    70.5  995.44    70.5 1008.04      70 1014.04    69.5  1024.6      69
 1036.88      69 1041.82    69.5 1055.45   71.29 1070.55    73.5 1078.59      74
 1092.19    74.5  1145.6      76 1225.17    77.5 1269.16      78  1291.2      78
#Mann= 3 , 0 , 0
       0    .035       0  270.55    .018       0  353.22    .035       0
Levee=-1,241.57,72.36261,-1,492.77,72.36261,	452,	451
Bank Sta=270.55,353.22
XS Rating Curve= 0 ,0
Exp/Cntr=0.3,0.1

Type RM Length L Ch R = 1 ,8372.053,72.42,108.66,144.91
XS GIS Cut Line= 6
    1079236.8122    1572529.6153    1079140.6199    1572728.0176
    1079096.0536    1572807.9575    1079149.5197     1572919.071
     1079160.612    1572940.2495    1078827.2364    1573784.8012
#Sta/Elev= 30
       0      73   57.73      73  129.66   72.54  240.63    72.5  266.01   70.69
  353.32   70.72  374.32   69.29  414.32   69.29  435.32   70.79  529.97   70.82
  553.46    72.5  725.27    72.5  844.52      72  984.74      72 1014.89    72.4
 1029.93   72.28 1066.06   71.17 1079.68    70.5 1106.94      70 1116.99      69
 1134.46      69  1138.6    69.5 1140.94      70  1150.4      73 1153.66   73.58
 1159.01      74 1253.53   76.49 1306.77      77 1352.15      78  1367.2      78
#Mann= 3 , 0 , 0
       0    .035       0  353.32    .018       0  435.32    .035       0
Levee=-1,244.96,72.19109,-1,551.01,72.32472,	452,	451
Bank Sta=353.32,435.32
XS Rating Curve= 0 ,0
Exp/Cntr=0.3,0.1

Type RM Length L Ch R = 1 ,8263.394,75.89,111.57,147.24
XS GIS Cut Line= 4
    1079207.1788    1572509.5069    1079114.7195    1572715.9643
    1078988.1435    1572987.9543    1078734.1028    1573749.8761
#Sta/Elev= 30
       0      73   62.84    72.5  245.85    72.5  271.62   70.66  388.31   70.66
  409.19   69.19  449.23   69.19  470.35   70.66  480.82   70.66  501.82   72.16
  526.22   72.16  526.96   71.92  687.74      72  756.24   71.72 1014.35      72
 1024.78      71 1037.96      69 1045.76    68.5 1051.26    68.5 1060.57      69
 1094.21      72 1105.86      72 1118.71      71 1131.58   70.92 1159.07   71.82
  1185.9    73.5  1222.2      75 1243.25   75.26  1278.4   76.23 1329.37   76.96
#Mann= 3 , 0 , 0
       0    .035       0  388.31    .018       0  470.35    .035       0
Levee=-1,250.61,72.15994,-1,501.81,72.15994,	452,	451
Bank Sta=388.31,470.35
XS Rating Curve= 0 ,0
Exp/Cntr=0.3,0.1

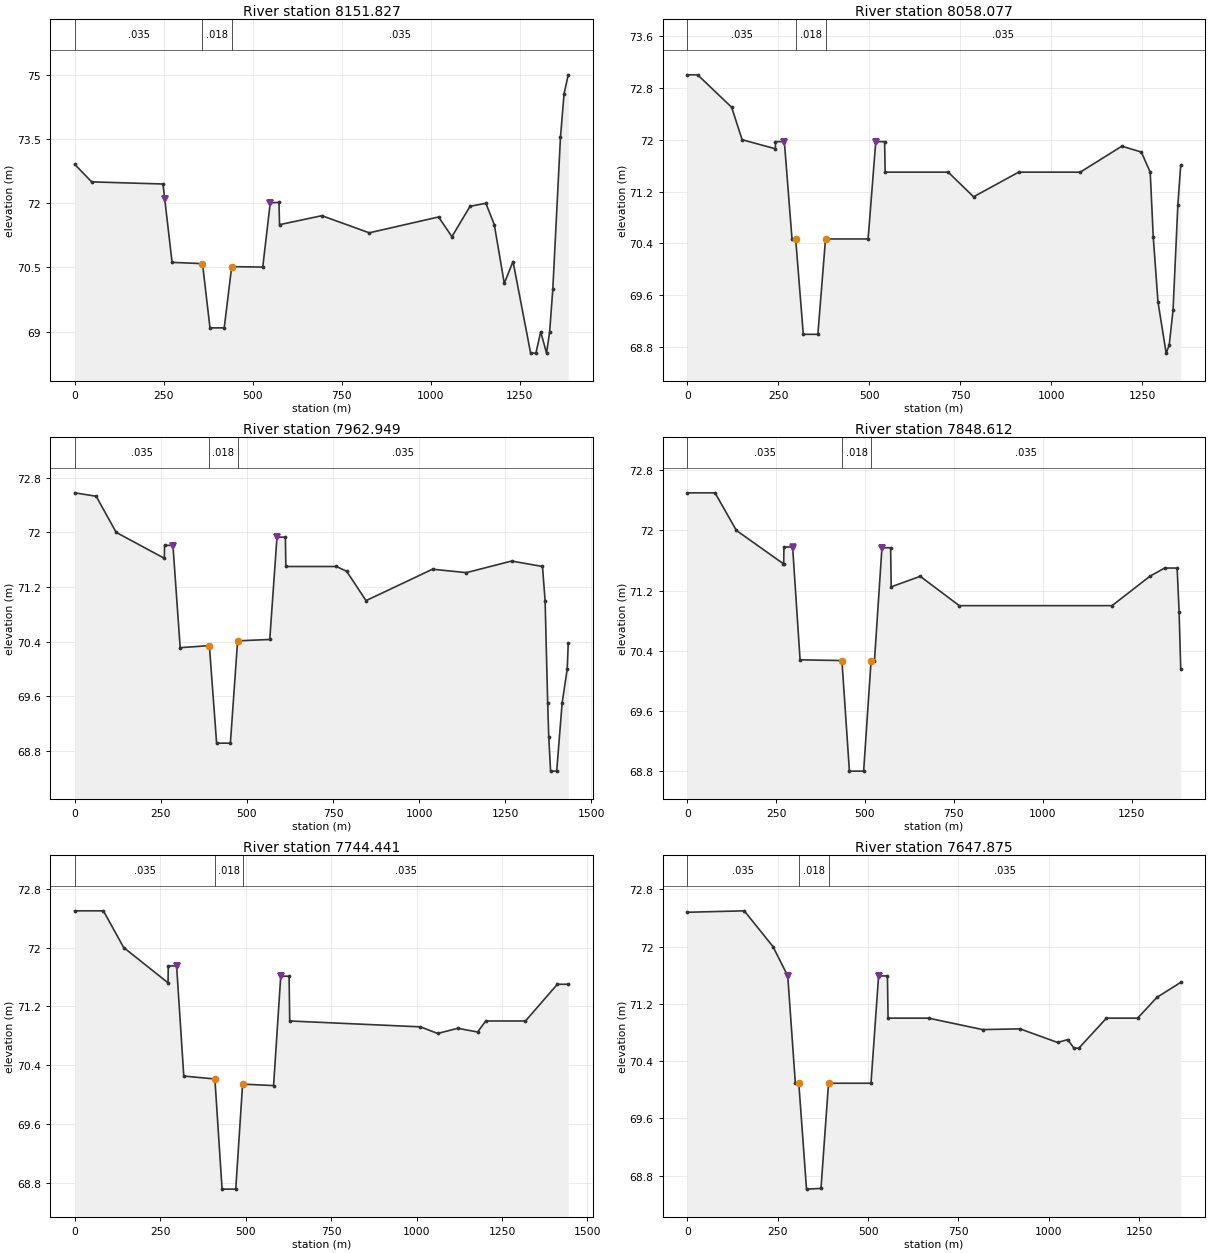
Type RM Length L Ch R = 1 ,8151.827,132.49,93.75,55.01
XS GIS Cut Line= 6
    1079179.6621    1572494.6902    1079087.3428     1572703.224
    1079045.2535    1572789.9658    1078932.8887    1572820.4592
    1078914.0199    1572841.8243    1078634.6193     1573714.951
#Sta/Elev= 30
       0   72.91   47.57    72.5  247.93   72.45  273.46   70.62   358.9   70.59
   379.9   69.09   419.9   69.09   440.9   70.52  528.14   70.51   549.2   72.01
  573.68   72.02  575.23    71.5  694.23   71.71  827.29   71.31 1022.04   71.68
 1059.43   71.22 1110.43   71.93 1154.79      72 1178.52    71.5 1206.48   70.13
 1231.08   70.64 1280.53    68.5 1295.36    68.5 1308.85      69 1325.22    68.5
 1333.96      69 1342.84      70 1364.31   73.54 1374.45   74.56 1386.14      75
#Mann= 3 , 0 , 0
       0    .035       0   358.9    .018       0   440.9    .035       0
Levee=-1,252.93,72.09,-1,549.29,72.01389,	452,	451
Bank Sta=358.9,440.9
XS Rating Curve= 0 ,0
Exp/Cntr=0.3,0.1

Type RM Length L Ch R = 1 ,8058.077,133.73,95.13,56.53
XS GIS Cut Line= 4
    1079064.8327    1572431.4018    1078954.4105    1572645.2909
    1078864.4802    1572883.4531     1078573.765     1573693.996
#Sta/Elev= 30
       0      73   28.62      73  122.09    72.5  150.84      72  242.23   71.86
  242.56   71.97  266.96   71.97  287.96   70.47  298.06   70.47  319.05      69
  359.06      69  380.13   70.47  497.16   70.47  518.16   71.97  542.56   71.97
  543.98    71.5  717.22    71.5  787.06   71.12  910.99    71.5 1080.33    71.5
 1194.57    71.9 1247.99   71.81 1272.48    71.5 1280.85    70.5 1293.84    69.5
 1316.32   68.71 1324.62   68.83 1335.22   69.37  1348.5      71 1356.39   71.61
#Mann= 3 , 0 , 0
       0    .035       0  298.06    .018       0  380.13    .035       0
Levee=-1,267.02,71.96507,-1,518.24,71.9697,	452,	451
Bank Sta=298.06,380.13
XS Rating Curve= 0 ,0
Exp/Cntr=0.3,0.1

Type RM Length L Ch R = 1 ,7962.949,78.48,114.34,150.19
XS GIS Cut Line= 6
    1078881.4231    1572348.1108    1078808.8085    1572598.7291
    1078784.9029    1572683.3915    1078852.9902    1572787.2213
    1078860.2564    1572814.6251    1078534.2891    1573687.5401
#Sta/Elev= 30
       0   72.58   62.27   72.53  120.53      72   260.3   71.62  260.85   71.81
  285.25   71.81  306.25   70.31  391.06   70.34  412.06   68.91  452.06   68.91
  473.06   70.41  566.41   70.43  587.41   71.93  611.82   71.93  613.12    71.5
  760.06    71.5  789.68   71.43  846.01      71 1039.03   71.46 1137.27   71.41
 1268.91   71.58 1358.38    71.5 1366.04      71 1373.51    69.5 1376.66      69
 1381.93    68.5 1399.68    68.5 1415.51    69.5 1430.31      70  1433.2   70.38
#Mann= 3 , 0 , 0
       0    .035       0  391.06    .018       0  473.06    .035       0
Levee=-1,285.33,71.8001,-1,587.45,71.93429,	452,	451
Bank Sta=391.06,473.06
XS Rating Curve= 0 ,0
Exp/Cntr=0.3,0.1

Type RM Length L Ch R = 1 ,7848.612,69.71,104.17,138.64
XS GIS Cut Line= 4
    1078856.8697    1572329.4841    1078785.7915    1572590.9508
    1078698.8347    1572878.1138    1078462.3223    1573660.4468
#Sta/Elev= 24
       0    72.5   78.19    72.5  138.34      72   269.6   71.56  271.41   71.56
  272.06   71.78  296.47   71.78  317.48   70.28  435.19   70.27  456.24    68.8
  496.27    68.8  517.26   70.27  526.77   70.27  547.78   71.77  572.19   71.77
  573.73   71.25  655.46   71.39   765.3      71 1195.07      71 1301.33   71.39
 1342.69    71.5  1378.2    71.5 1383.68   70.92  1388.3   70.16
#Mann= 3 , 0 , 0
       0    .035       0  435.19    .018       0  517.26    .035       0
Levee=-1,296.55,71.77283,-1,547.83,71.7709,	452,	451
Bank Sta=435.19,517.26
XS Rating Curve= 0 ,0
Exp/Cntr=0.3,0.1

Type RM Length L Ch R = 1 ,7744.441,136.14,96.57,56.98
XS GIS Cut Line= 6
     1078809.668    1572315.7257    1078755.1603    1572583.9023
    1078732.1978    1572678.9464    1078622.8718     1572729.903
    1078603.9276    1572741.1766    1078396.2822    1573647.3234
#Sta/Elev= 24
       0    72.5   83.96    72.5  143.29      72  273.01   71.52  273.66   71.75
  298.06   71.75  319.07   70.25  410.06   70.21  431.06   68.71  471.06   68.71
  491.13   70.14  492.06   70.14  581.73   70.12   602.7   71.61  627.12   71.61
  628.96      71 1011.28   70.92 1061.62   70.83 1120.55    70.9 1178.57   70.85
 1202.39      71  1318.7      71 1411.92    71.5 1443.73    71.5
#Mann= 3 , 0 , 0
       0    .035       0  410.06    .018       0  492.06    .035       0
Levee=-1,298.06,71.74581,-1,602.75,71.61491,	452,	451
Bank Sta=410.06,492.06
XS Rating Curve= 0 ,0
Exp/Cntr=0.3,0.1

Type RM Length L Ch R = 1 ,7647.875,123.11,84.42,45.74
XS GIS Cut Line= 4
     1078660.612     1572303.449    1078611.3139    1572552.2751
    1078568.3847    1572803.1983    1078364.2781    1573635.2584
#Sta/Elev= 24
       0   72.48  157.71    72.5  237.24      72  278.04   71.59  299.04   70.09
  308.61   70.09  329.93   68.61  369.98   68.62  390.79   70.09  508.24   70.09
  529.28   71.59  553.73   71.59   555.5      71  667.43      71  816.89   70.84
  920.58   70.85 1024.31   70.66 1052.44    70.7 1069.75   70.58 1083.05   70.58
  1159.5      71 1245.72      71 1298.93   71.29 1364.96    71.5
#Mann= 3 , 0 , 0
       0    .035       0  308.61    .018       0  390.79    .035       0
Levee=-1,278.06,71.58556,-1,529.34,71.58855,	452,	451
Bank Sta=308.61,390.79
XS Rating Curve= 0 ,0
Exp/Cntr=0.3,0.1