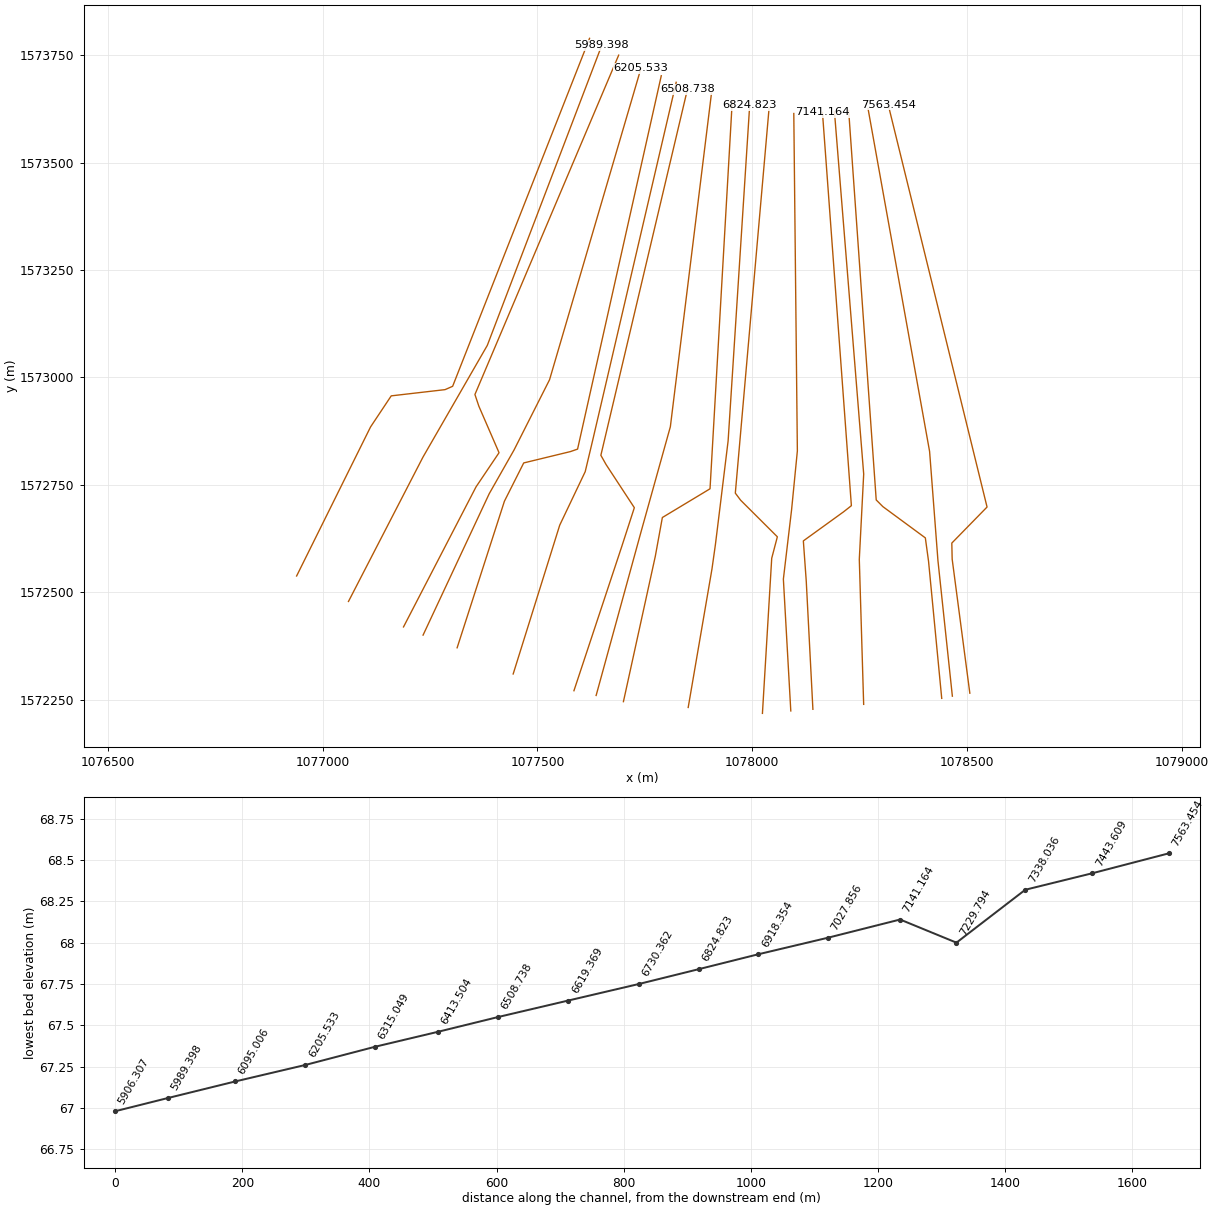
HEC-RAS study HECRAS_v2.prj: HECRAS_v2

--- HECRAS_v2.g01 (geometry) --- (continued)

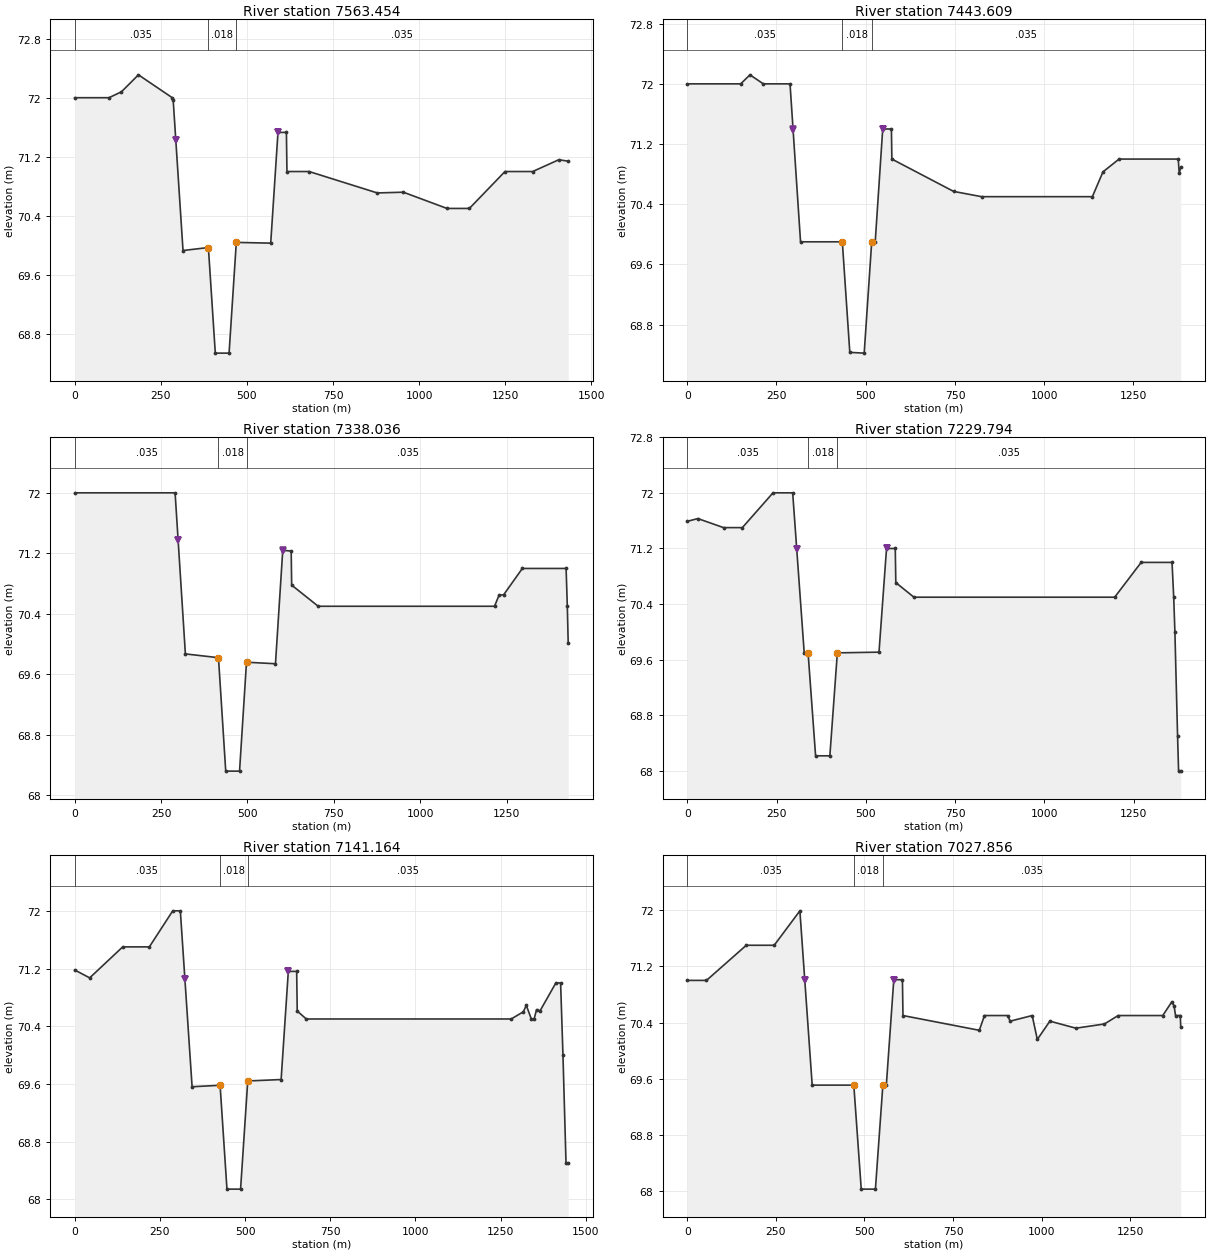
Type RM Length L Ch R = 1 ,7563.454,84.95,119.85,154.72
XS GIS Cut Line= 5
     1078506.095     1572265.349    1078465.0065    1572577.1945
     1078464.185    1572614.5997    1078546.1793     1572698.458
    1078316.2297    1573634.4117
#Sta/Elev= 25
       0      72   99.46      72  135.64   72.08  185.06   72.31  283.25      72
  285.92   71.97  314.49   69.93  387.24   69.97  388.18   69.97  408.24   68.54
  448.24   68.54  469.24   70.04  569.16   70.03  590.24   71.53  614.73   71.53
  616.32      71  680.66      71  878.59   70.71  954.32   70.72 1081.03    70.5
 1146.05    70.5 1249.41      71 1329.96      71 1405.85   71.16 1433.03   71.14
#Mann= 3 , 0 , 0
       0    .035       0  387.24    .018       0  469.24    .035       0
Levee=-1,293.57,71.42873,-1,590.23,71.52978,	452,	451
Bank Sta=387.24,469.24
XS Rating Curve= 0 ,0
Exp/Cntr=0.3,0.1

Type RM Length L Ch R = 1 ,7443.609,70.34,105.57,140.83
XS GIS Cut Line= 4
     1078465.455    1572258.3639    1078431.9017    1572573.9409
    1078412.4907    1572827.8406    1078269.2396    1573625.5217
#Sta/Elev= 22
       0      72  149.71      72  175.66   72.12   213.1      72  287.93      72
  317.36    69.9  434.41    69.9  455.37   68.43   495.7   68.42  516.72    69.9
  526.57    69.9  547.57    71.4  571.97    71.4  573.18      71  746.15   70.57
  824.51    70.5  1134.9    70.5 1164.56   70.83  1209.7      71 1375.52      71
 1378.08   70.81 1382.44   70.89
#Mann= 3 , 0 , 0
       0    .035       0  434.41    .018       0  516.72    .035       0
Levee=-1,296.43,71.39285,-1,547.59,71.40041,	452,	451
Bank Sta=434.41,516.72
XS Rating Curve= 0 ,0
Exp/Cntr=0.3,0.1

Type RM Length L Ch R = 1 ,7338.036,148.73,108.24,67.75
XS GIS Cut Line= 6
    1078440.6899    1572253.2839    1078410.0467     1572572.214
    1078402.5898    1572626.6647     1078303.739    1572699.4352
    1078288.2896    1572714.9299    1078224.1545    1573621.0767
#Sta/Elev= 20
       0      72  290.56      72  320.33   69.87  416.11   69.82  437.11   68.32
  477.11   68.32   497.2   69.76  498.11   69.76   581.1   69.74  602.14   71.24
  626.59   71.23  627.94   70.78  704.78    70.5 1215.23    70.5  1228.5   70.65
 1241.25   70.65 1295.63      71 1422.31      71 1425.83    70.5  1428.4   70.01
#Mann= 3 , 0 , 0
       0    .035       0  416.11    .018       0  498.11    .035       0
Levee=-1,299.31,71.37502,-1,602.22,71.23528,	452,	451
Bank Sta=416.11,498.11
XS Rating Curve= 0 ,0
Exp/Cntr=0.3,0.1

Type RM Length L Ch R = 1 ,7229.794,125.27,88.63,51.99
XS GIS Cut Line= 4
    1078259.0796    1572239.3139    1078248.9277    1572576.7524
    1078259.1448    1572775.2182    1078191.1344    1573617.9017
#Sta/Elev= 24
       0   71.59   29.72   71.63   101.6    71.5   154.3    71.5  240.12      72
   295.2      72  327.46    69.7  338.32    69.7  359.36   68.22   399.3   68.22
  420.26    69.7   536.9   69.71  557.97    71.2  582.45    71.2  583.94   70.71
   634.6    70.5 1196.78    70.5 1270.95      71 1357.37      71 1362.04    70.5
 1365.39      70 1372.89    68.5 1375.74      68 1381.74      68
#Mann= 3 , 0 , 0
       0    .035       0  338.32    .018       0  420.26    .035       0
Levee=-1,306.5,71.19247,-1,558.01,71.2039,	452,	451
Bank Sta=338.32,420.26
XS Rating Curve= 0 ,0
Exp/Cntr=0.3,0.1

Type RM Length L Ch R = 1 ,7141.164,78.58,113.31,148.04
XS GIS Cut Line= 6
    1078140.9693    1572227.8839    1078125.4875    1572526.2204
    1078118.7443    1572619.6797    1078212.2914    1572687.2832
    1078230.5045    1572701.5948    1078163.1944    1573616.6317
#Sta/Elev= 29
       0   71.18   43.91   71.07  140.93    71.5  219.06    71.5  287.77      72
  310.04      72  344.53   69.56  425.86   69.58  426.73   69.58  446.86   68.14
  486.86   68.14  507.86   69.64  605.87   69.66  626.97   71.16  651.49   71.16
  653.15   70.61  679.69    70.5 1281.23    70.5 1316.99    70.6 1325.47   70.69
 1340.26    70.5 1348.49    70.5 1355.67   70.63 1365.51   70.61 1412.31      71
 1426.23      71 1433.13      70 1442.11    68.5 1448.53    68.5
#Mann= 3 , 0 , 0
       0    .035       0  425.86    .018       0  507.86    .035       0
Levee=-1,323.4,71.05342,-1,626.99,71.16149,	452,	451
Bank Sta=425.86,507.86
XS Rating Curve= 0 ,0
Exp/Cntr=0.3,0.1

Type RM Length L Ch R = 1 ,7027.856,73.22,109.5,145.78
XS GIS Cut Line= 5
    1078089.5342    1572224.0739    1078072.2662    1572530.7353
    1078091.3989    1572692.3778    1078104.8158    1572829.0109
    1078096.5192    1573614.0916
#Sta/Elev= 30
       0      71   54.24      71  166.58    71.5  245.34    71.5  317.79   71.99
   352.5   69.51  469.92   69.51  490.89   68.03   530.9   68.03  551.91   69.51
  561.72   69.51  582.72   71.01  607.12   71.01  608.66    70.5  824.03   70.29
  838.62    70.5  903.76    70.5  911.13   70.42   973.2    70.5  987.69   70.16
 1023.09   70.42 1096.64   70.32 1177.09   70.38 1215.63    70.5 1341.61    70.5
 1366.45   70.69 1373.55   70.64 1377.63    70.5 1391.08    70.5 1392.33   70.34
#Mann= 3 , 0 , 0
       0    .035       0  469.92    .018       0  551.91    .035       0
Levee=-1,331.55,71.00288,-1,582.81,71.00985,	452,	451
Bank Sta=469.92,551.91
XS Rating Curve= 0 ,0
Exp/Cntr=0.3,0.1

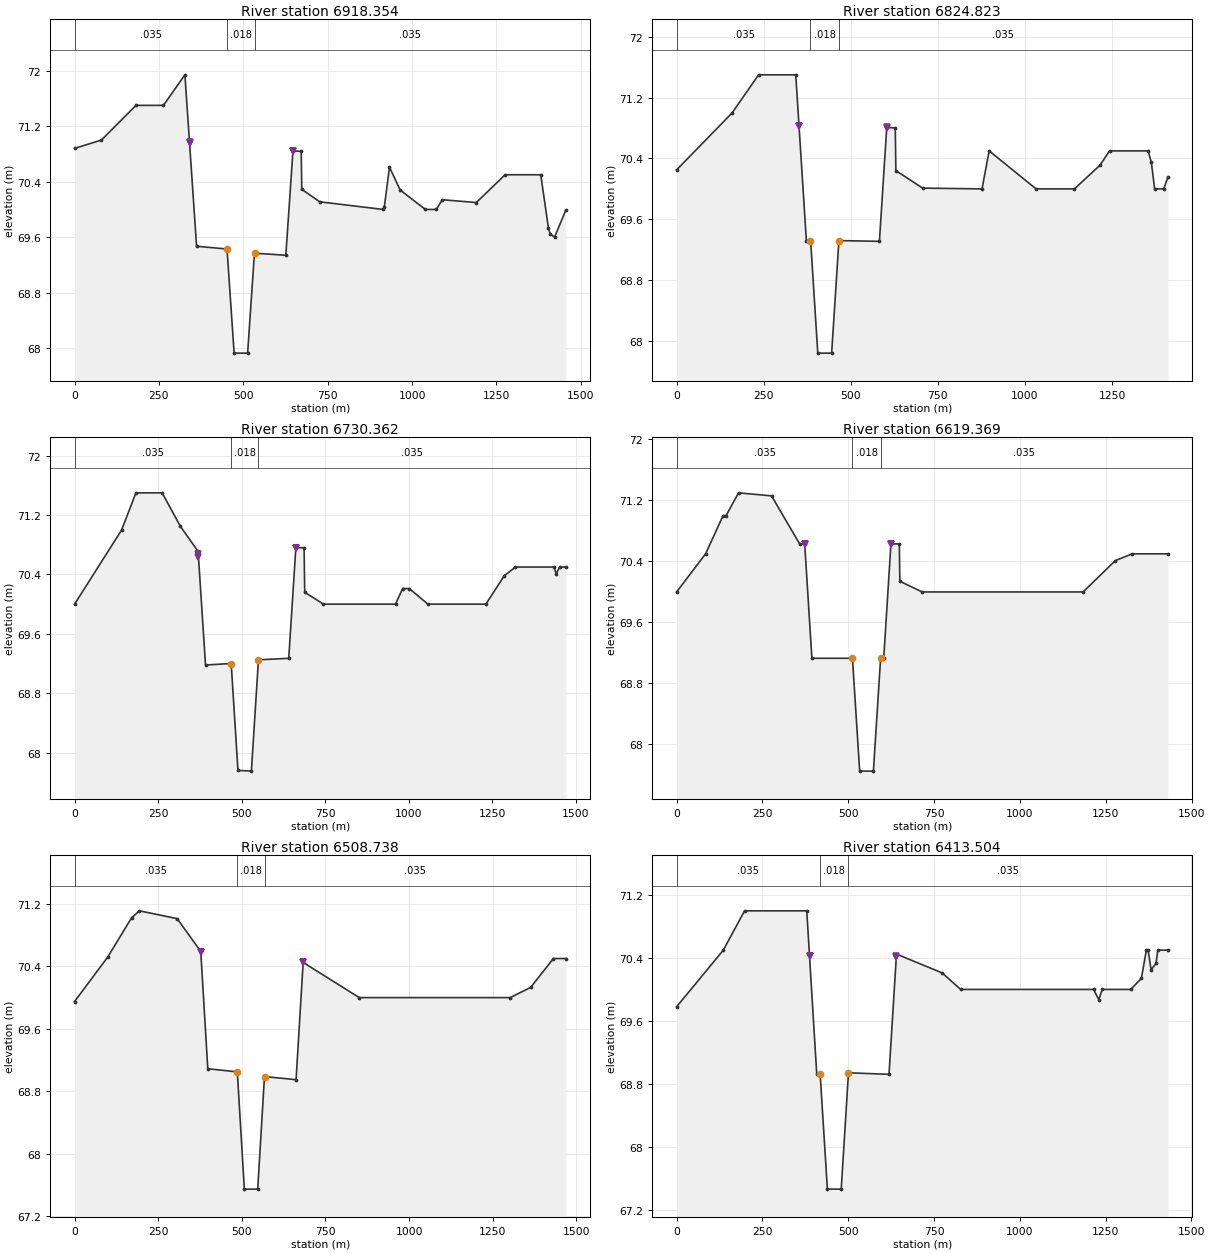
Type RM Length L Ch R = 1 ,6918.354,130.83,93.53,56.23
XS GIS Cut Line= 6
    1078023.5364    1572218.3589    1078045.1515    1572579.2561
    1078058.2498    1572629.2047    1077972.8051    1572714.3585
    1077960.4596    1572730.8049    1078039.1998    1573628.6967
#Sta/Elev= 30
       0   70.88   79.45      71  181.95    71.5   263.3    71.5   326.9   71.94
  361.54   69.47  451.75   69.43  472.77   67.93   512.8   67.93  532.96   69.37
  533.81   69.37     626   69.34  647.09   70.84  671.59   70.84  673.27   70.29
  726.65   70.11  914.95      70  917.75   70.03  933.12   70.61  964.93   70.28
 1039.66      70 1071.76      70 1089.87   70.14 1190.63    70.1 1275.72    70.5
  1381.5    70.5 1404.07   69.74 1409.14   69.65 1422.37    69.6 1455.72   69.99
#Mann= 3 , 0 , 0
       0    .035       0  451.75    .018       0  533.81    .035       0
Levee=-1,340.59,70.9677,-1,647.12,70.84079,	452,	451
Bank Sta=451.75,533.81
XS Rating Curve= 0 ,0
Exp/Cntr=0.3,0.1

Type RM Length L Ch R = 1 ,6824.823,131.59,94.46,57.33
XS GIS Cut Line= 6
    1077850.8161    1572232.1172    1077906.1448    1572554.4187
    1077914.0826    1572610.7491     1077924.109    1572692.1077
    1077943.7248     1572852.662     1077993.903    1573633.3534
#Sta/Elev= 26
       0   70.25  159.44      71  235.22    71.5  341.95    71.5  372.44   69.32
   383.9   69.32  384.65   69.32  405.23   67.84  444.99   67.84  465.88   69.32
  582.12   69.31  603.17   70.81  627.63    70.8  629.35   70.24  706.34   70.01
  876.63      70  897.14    70.5 1031.73      70 1141.79      70 1215.01   70.31
 1242.65    70.5 1353.36    70.5 1362.69   70.35 1372.04      70 1398.14      70
 1409.93   70.15
#Mann= 3 , 0 , 0
       0    .035       0   383.9    .018       0  465.88    .035       0
Levee=-1,351.45,70.82193,-1,603.18,70.8055,	452,	451
Bank Sta=383.9,465.88
XS Rating Curve= 0 ,0
Exp/Cntr=0.3,0.1

Type RM Length L Ch R = 1 ,6730.362,79.99,110.99,142
XS GIS Cut Line= 6
    1077700.1091    1572245.6639    1077774.2871    1572583.9064
    1077790.7026    1572674.0781    1077886.8148    1572731.9604
    1077901.6162    1572740.9649    1077953.2629      1573641.82
#Sta/Elev= 28
       0      70  140.82      71  183.49    71.5  261.92    71.5  316.27   71.05
  369.58   70.71  391.74   69.18  467.69    69.2  468.57    69.2  488.81   67.76
  529.02   67.75  550.13   69.25  640.79   69.27  662.05   70.76  686.75   70.76
  688.56   70.16  744.64      70  960.28      70  981.52   70.21  1001.4   70.21
 1057.27      70 1230.67      70 1285.31   70.38 1319.17    70.5 1434.49    70.5
 1441.04   70.41  1451.4    70.5 1469.79    70.5
#Mann= 3 , 0 , 0
       0    .035       0  467.69    .018       0  550.13    .035       0
Levee=-1,370.74,70.6739,-1,662.07,70.76231,	452,	451
Bank Sta=467.69,550.13
XS Rating Curve= 0 ,0
Exp/Cntr=0.3,0.1

Type RM Length L Ch R = 1 ,6619.369,75.69,110.63,145.57
XS GIS Cut Line= 4
     1077636.609    1572260.0573    1077740.8731    1572639.9945
    1077809.3023    1572885.2722    1077905.0028    1573661.2934
#Sta/Elev= 22
       0      70   84.39    70.5   135.2      71  143.89      71  180.33    71.3
  276.47   71.26  358.27   70.63     373   70.63  393.98   69.13  512.11   69.13
  533.12   67.65  573.12   67.65  594.11   69.13   603.2   69.13   624.2   70.63
   648.6   70.63  650.08   70.14  715.19      70 1183.83      70 1277.34   70.41
 1326.95    70.5 1430.53    70.5
#Mann= 3 , 0 , 0
       0    .035       0  512.11    .018       0  594.11    .035       0
Levee=-1,373.04,70.6272,-1,624.23,70.62787,	452,	451
Bank Sta=512.11,594.11
XS Rating Curve= 0 ,0
Exp/Cntr=0.3,0.1

Type RM Length L Ch R = 1 ,6508.738,137.26,95.23,53.18
XS GIS Cut Line= 6
    1077584.9622     1572271.064    1077696.0224    1572605.9842
    1077725.5092    1572696.9381    1077659.7331    1572797.3003
    1077647.6157    1572818.8584    1077849.1227    1573670.6068
#Sta/Elev= 19
       0   69.95   99.18   70.52  170.27   71.02  193.71   71.11  306.69   71.01
  377.18   70.59  398.18   69.09  486.46   69.05  507.46   67.55  547.46   67.55
  567.62   68.99  568.46   68.99   662.1   68.95  683.28   70.45     851      70
 1302.36      70 1363.21   70.13 1431.56    70.5 1468.45    70.5
#Mann= 3 , 0 , 0
       0    .035       0  486.46    .018       0  568.46    .035       0
Levee=-1,377.26,70.58814,-1,683.35,70.45036,	452,	451
Bank Sta=486.46,568.46
XS Rating Curve= 0 ,0
Exp/Cntr=0.3,0.1

Type RM Length L Ch R = 1 ,6413.504,134.85,98.46,62.09
XS GIS Cut Line= 5
    1077443.5686    1572310.0107    1077551.8597    1572656.1842
     1077611.188    1572780.7703    1077628.1423    1572851.8785
     1077822.876    1573686.6935
#Sta/Elev= 24
       0   69.78  136.03    70.5  197.96      71  379.14      71  408.15   68.93
  418.07   68.93  439.24   67.46  479.53   67.46  500.71   68.94  618.79   68.92
  640.57   70.45  773.68   70.21  827.62      70 1214.78      70 1230.02   69.87
 1239.88      70 1322.84      70 1353.98   70.14 1368.61    70.5 1373.65    70.5
 1382.39   70.25  1396.7   70.33 1401.82    70.5 1431.03    70.5
#Mann= 3 , 0 , 0
       0    .035       0  418.07    .018       0  500.71    .035       0
Levee=-1,387.18,70.42523,-1,640.1,70.4221,	452,	451
Bank Sta=418.07,500.71
XS Rating Curve= 0 ,0
Exp/Cntr=0.3,0.1

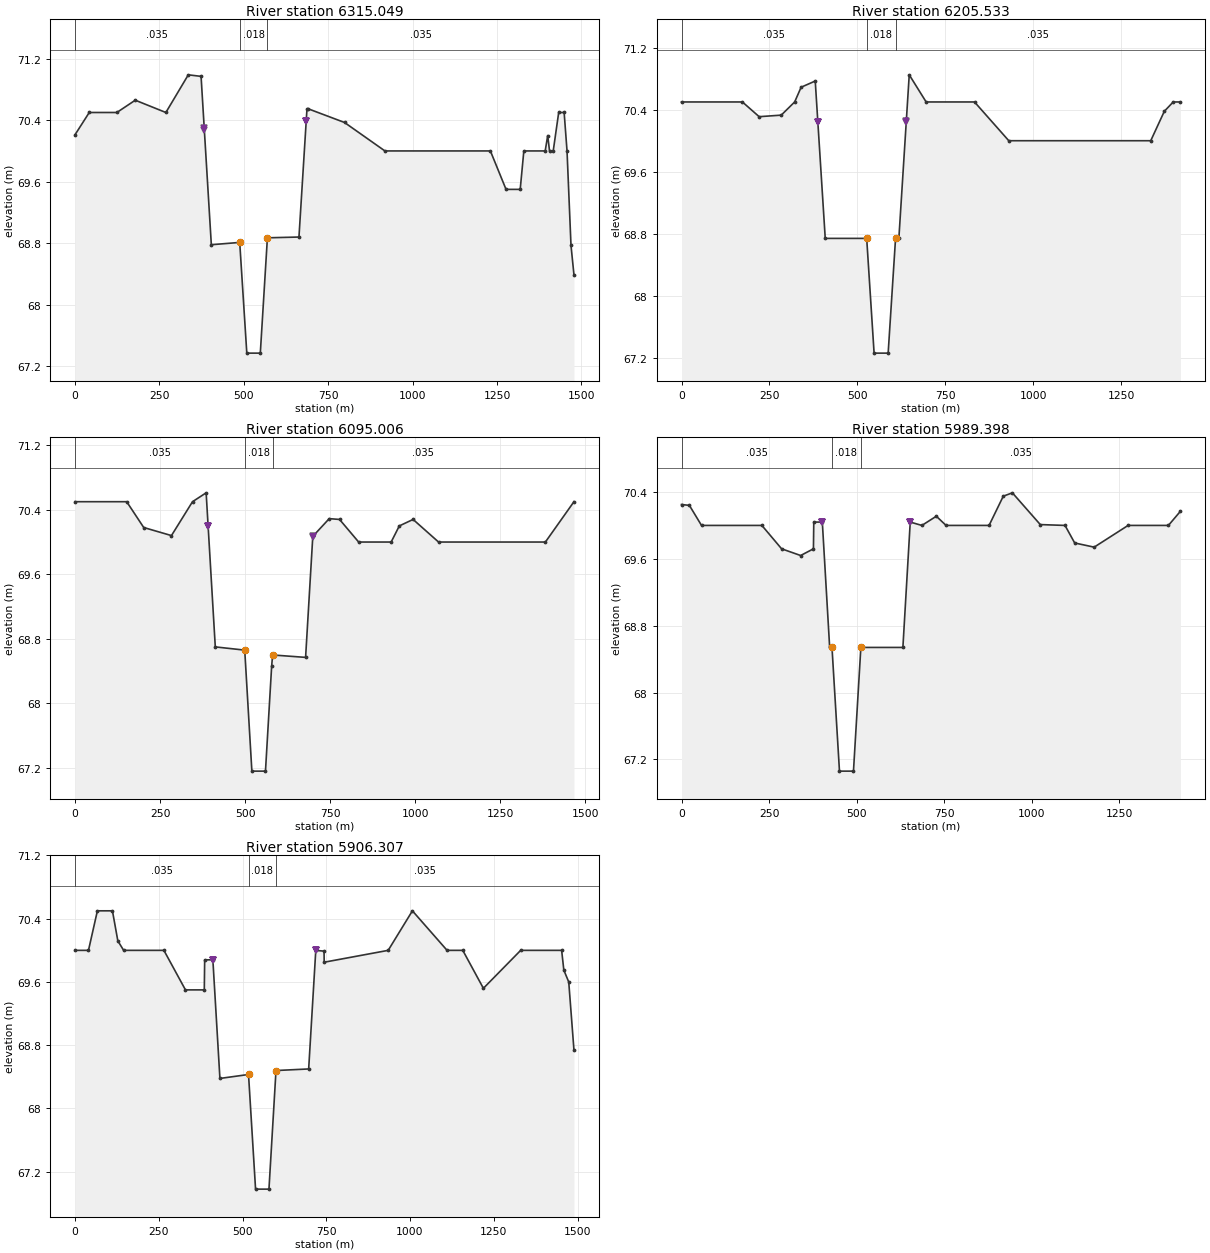
Type RM Length L Ch R = 1 ,6315.049,74.08,109.52,144.96
XS GIS Cut Line= 6
    1077313.1817    1572370.9708    1077423.2416    1572712.0683
     1077468.122    1572801.0784    1077576.7283    1572827.4692
    1077593.4289    1572833.2518    1077788.1626    1573701.9335
#Sta/Elev= 30
       0   70.21   42.21    70.5  123.98    70.5  178.51   70.66  269.18    70.5
  335.58   70.99  373.42   70.97   403.8   68.78  487.87   68.81  508.87   67.37
  548.87   67.37  569.87   68.87  663.35   68.88  686.98   70.54  689.53   70.55
  798.33   70.37  917.92      70 1230.29      70 1276.63    69.5 1318.59    69.5
 1329.36      70  1392.6      70 1400.07    70.2 1405.43      70 1416.39      70
 1432.59    70.5 1448.72    70.5 1457.27      70 1469.02   68.77 1477.78   68.39
#Mann= 3 , 0 , 0
       0    .035       0  487.87    .018       0  569.87    .035       0
Levee=-1,382.82,70.27781,-1,684.77,70.3833,	452,	451
Bank Sta=487.87,569.87
XS Rating Curve= 0 ,0
Exp/Cntr=0.3,0.1

Type RM Length L Ch R = 1 ,6205.533,74.56,110.53,146.5
XS GIS Cut Line= 5
    1077233.9476    1572400.4631    1077387.8418    1572729.4454
    1077445.6147    1572831.2056    1077528.2412    1572994.6647
    1077740.8903    1573719.1491
#Sta/Elev= 21
       0    70.5   173.1    70.5  220.77   70.31  283.52   70.33   321.7    70.5
  340.03   70.69  380.17   70.77  408.61   68.74  526.43   68.74  547.49   67.26
  587.46   67.26   608.5   68.74   617.9   68.74  647.39   70.85  695.43    70.5
  832.92    70.5   930.4      70 1333.93      70 1372.57   70.38 1397.81    70.5
 1418.42    70.5
#Mann= 3 , 0 , 0
       0    .035       0  526.43    .018       0   608.5    .035       0
Levee=-1,387.62,70.23576,-1,638.97,70.24936,	452,	451
Bank Sta=526.43,608.5
XS Rating Curve= 0 ,0
Exp/Cntr=0.3,0.1

Type RM Length L Ch R = 1 ,6095.006,143.8,105.61,67.44
XS GIS Cut Line= 6
    1077188.4392    1572419.5131     1077357.076    1572745.2403
    1077410.6896    1572824.8556    1077363.6318    1572933.3258
    1077354.5979    1572960.3226    1077689.0319    1573749.8408
#Sta/Elev= 23
       0    70.5  151.99    70.5  202.07   70.18  283.61   70.08   345.5    70.5
  385.59   70.61  412.47    68.7  499.01   68.66  520.01   67.16  560.01   67.16
  578.16   68.46  581.01    68.6  677.97   68.57  699.13   70.07  747.43   70.29
  777.84   70.28  833.95      70  929.52      70  953.49    70.2  994.02   70.28
  1068.9      70 1382.95      70 1466.91    70.5
#Mann= 3 , 0 , 0
       0    .035       0  499.01    .018       0  581.01    .035       0
Levee=-1,391.31,70.20357,-1,699.13,70.06611,	452,	451
Bank Sta=499.01,581.01
XS Rating Curve= 0 ,0
Exp/Cntr=0.3,0.1

Type RM Length L Ch R = 1 ,5989.398,121.37,83.09,44.79
XS GIS Cut Line= 4
    1077060.3806    1572478.7799    1077233.6889    1572814.6025
    1077383.3932    1573074.5806    1077649.8734    1573773.1242
#Sta/Elev= 29
       0   70.25   22.52   70.24   57.17      70  229.63      70  286.03   69.72
  340.42   69.64  376.94   69.72  377.91   70.04  402.31   70.04  423.31   68.54
  429.95   68.54  451.32   67.06  491.32   67.06  512.44   68.54  632.51   68.54
  653.51   70.04  686.79      70  728.05   70.11  755.84      70  878.72      70
  919.33   70.35  945.31   70.39 1025.05   70.01 1095.71      70 1123.34   69.79
 1179.03   69.74 1275.93      70 1391.12      70 1425.55   70.17
#Mann= 3 , 0 , 0
       0    .035       0  429.95    .018       0  512.44    .035       0
Levee=-1,402.31,70.04148,-1,653.5,70.04148,	452,	451
Bank Sta=429.95,512.44
XS Rating Curve= 0 ,0
Exp/Cntr=0.3,0.1

Type RM Length L Ch R = 1 ,5906.307,81.06,119.33,157.59
XS GIS Cut Line= 6
    1076939.7304    1572538.0467    1077111.7443    1572884.8224
    1077159.8641    1572957.1476    1077285.0474    1572971.6098
    1077302.7394    1572979.3726    1077621.2984    1573788.9992
#Sta/Elev= 30
       0      70   40.27      70   66.86    70.5  111.76    70.5  127.91   70.12
  145.25      70   265.4      70  329.76    69.5  385.96    69.5  387.09   69.88
  411.55   69.88  432.59   68.38  517.98   68.43  538.98   66.98  578.98   66.98
  599.98   68.48  697.51    68.5  718.74      70   743.4   69.99  743.84   69.85
  934.84      70 1007.15    70.5 1110.66      70 1157.53      70 1219.02   69.52
 1330.28      70  1452.6      70 1459.13   69.75 1473.79    69.6 1489.34   68.74
#Mann= 3 , 0 , 0
       0    .035       0  517.98    .018       0  599.98    .035       0
Levee=-1,411.54,69.87965,-1,718.73,69.99842,	452,	451
Bank Sta=517.98,599.98
XS Rating Curve= 0 ,0
Exp/Cntr=0.3,0.1