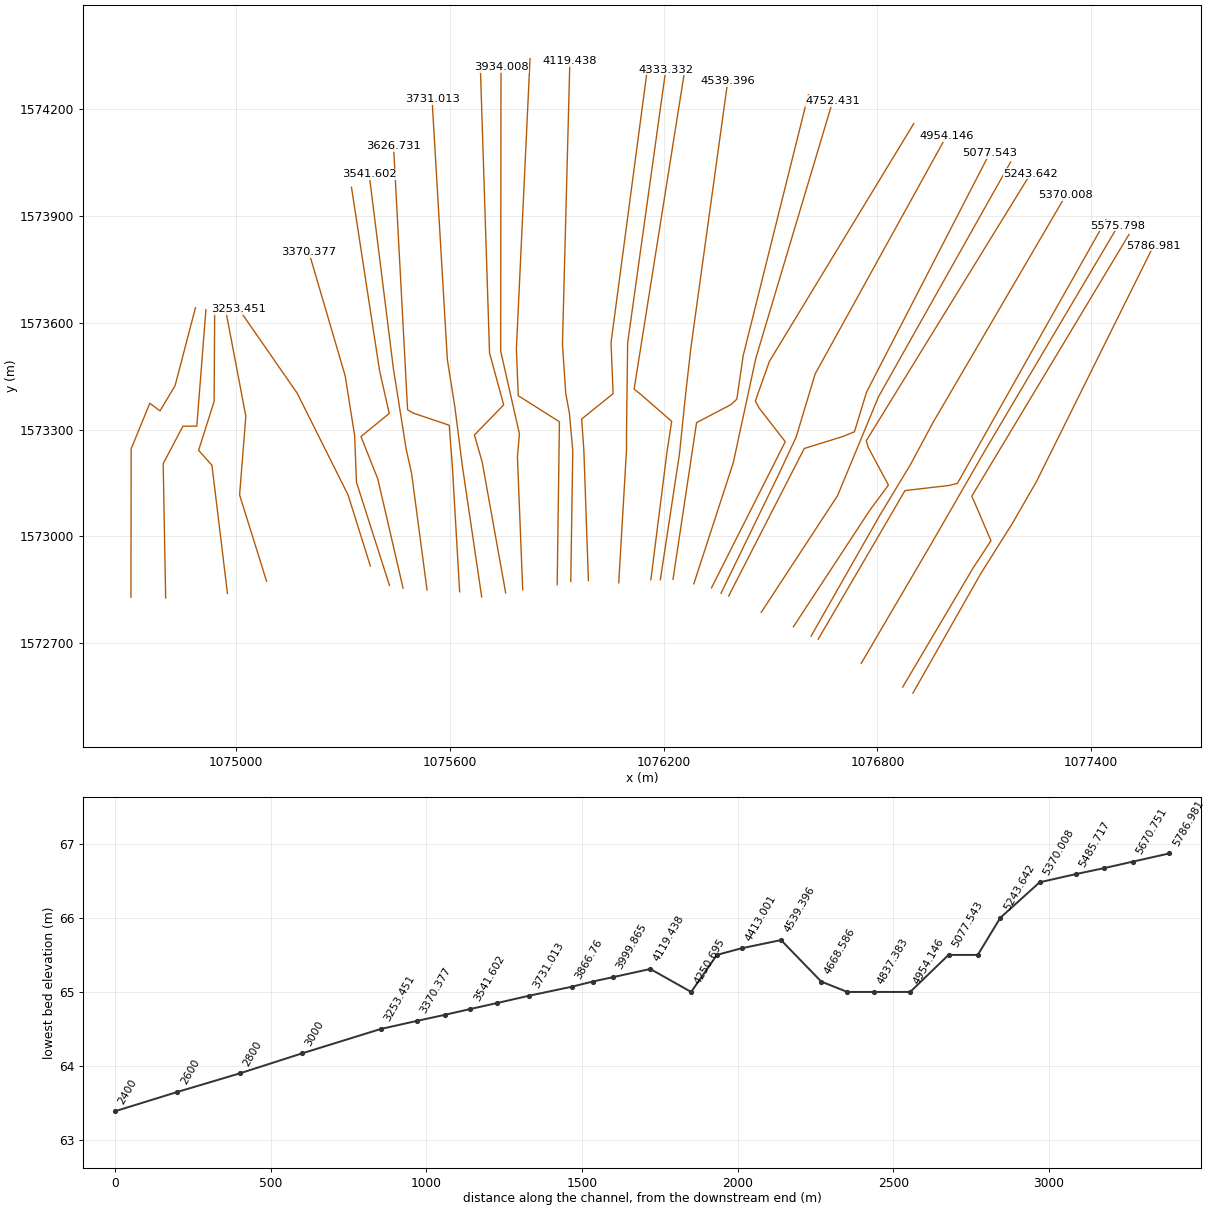
HEC-RAS study HECRAS_v2.prj: HECRAS_v2

--- HECRAS_v2.g01 (geometry) --- (continued)

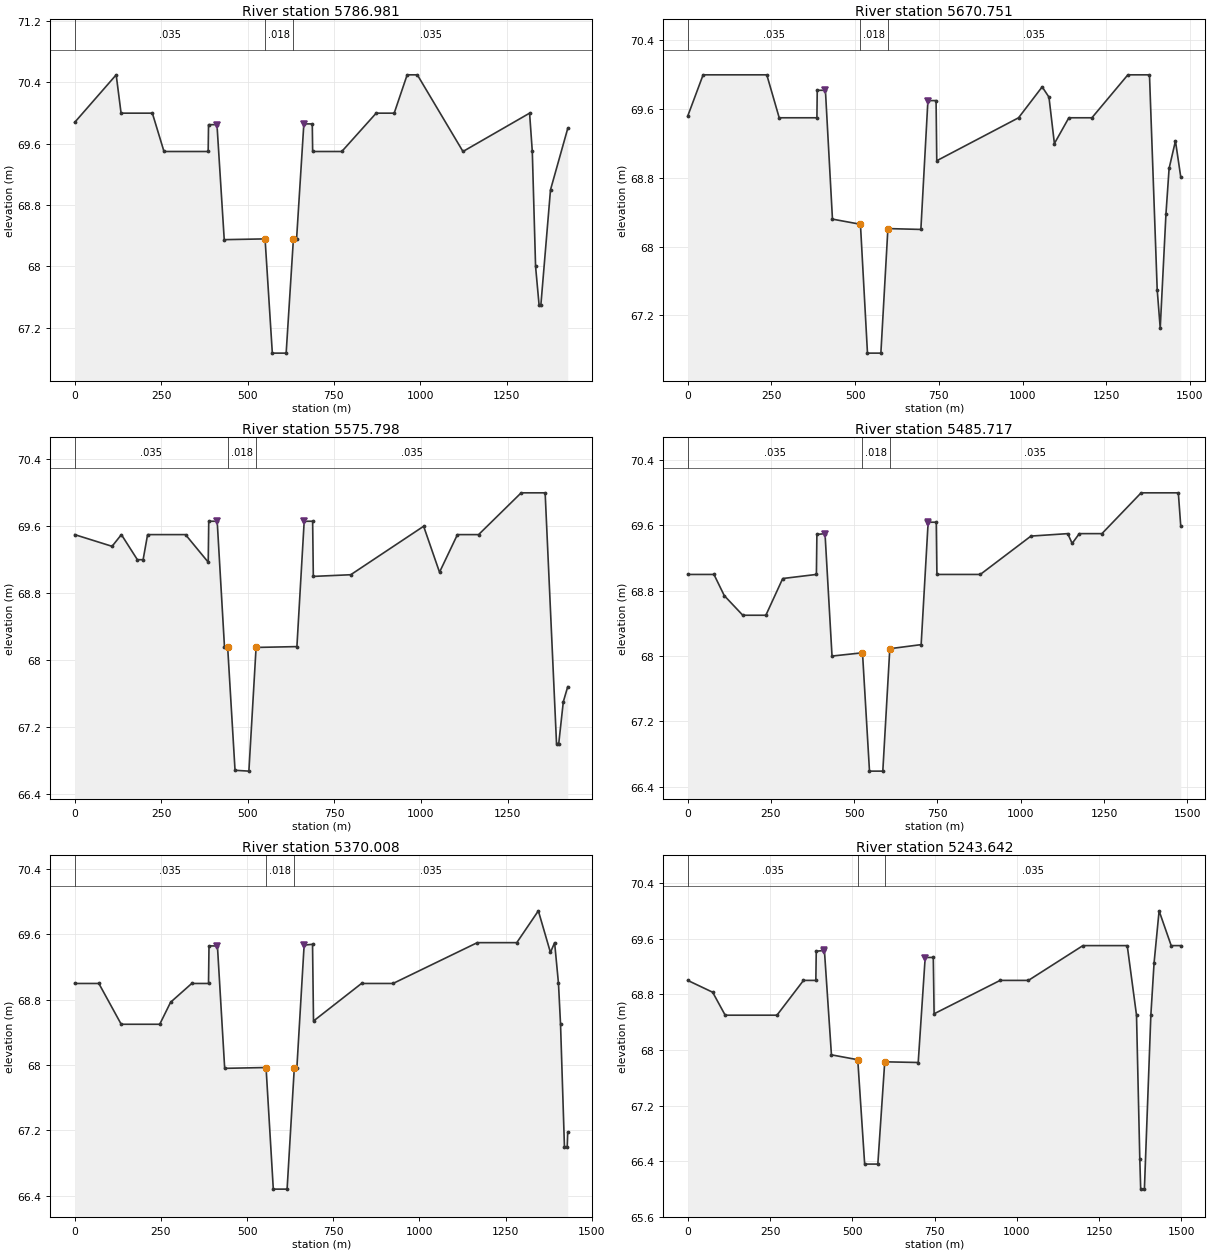
Type RM Length L Ch R = 1 ,5786.981,78.24,116.23,154.22
XS GIS Cut Line= 5
    1076899.5136    1572560.2718    1077090.7895    1572896.8889
    1077177.9757    1573035.2595     1077246.132    1573153.6204
    1077574.7316    1573815.4576
#Sta/Elev= 30
       0   69.88  120.01    70.5  134.18      70  224.66      70  258.32    69.5
  386.12    69.5  387.17   69.85  411.59   69.85   432.6   68.35  550.71   68.36
  571.73   66.87  611.73   66.87  632.72   68.36   641.9   68.36   662.9   69.86
   687.3   69.86  688.37    69.5  772.67    69.5   872.1      70  924.27      70
  961.77    70.5  991.19    70.5 1123.24    69.5 1315.92      70 1323.77    69.5
 1333.25      68 1343.32    67.5  1348.6    67.5 1376.42      69 1426.22    69.8
#Mann= 3 , 0 , 0
       0    .035       0  550.71    .018       0  632.72    .035       0
Levee=-1,411.59,69.85081,-1,662.9,69.85725,	452,	451
Bank Sta=550.71,632.72
XS Rating Curve= 0 ,0
Exp/Cntr=0.3,0.1

Type RM Length L Ch R = 1 ,5670.751,132.94,94.95,56.97
XS GIS Cut Line= 6
    1076870.9386    1572577.2051     1077067.716    1572910.1754
    1077118.5891    1572987.8393     1077072.109    1573096.5388
    1077064.6139    1573112.7229    1077505.9398    1573847.2077
#Sta/Elev= 30
       0   69.52   45.93      70  236.11      70   273.2    69.5  385.81    69.5
  386.77   69.82  411.21   69.82  432.24   68.32  515.83   68.26  536.83   66.76
  576.83   66.76  597.83   68.21   696.3    68.2  717.31    69.7  741.71    69.7
  743.77      69  988.08    69.5 1058.63   69.86 1078.89   69.74 1095.12    69.2
 1138.25    69.5 1207.16    69.5 1314.52      70 1379.11      70 1402.13    67.5
 1411.17   67.05 1428.32   68.38  1437.7   68.91 1456.66   69.23 1472.54   68.81
#Mann= 3 , 0 , 0
       0    .035       0  515.83    .018       0  597.83    .035       0
Levee=-1,411.21,69.82031,-1,717.31,69.70021,	452,	451
Bank Sta=515.83,597.83
XS Rating Curve= 0 ,0
Exp/Cntr=0.3,0.1

Type RM Length L Ch R = 1 ,5575.798,128.33,90.08,51.83
XS GIS Cut Line= 4
    1076754.5217    1572643.8803    1076950.2991    1572977.7881
    1077100.0034    1573237.7662    1077475.2481    1573871.5494
#Sta/Elev= 30
       0    69.5   107.9   69.36  134.82    69.5     181    69.2  197.57    69.2
   210.5    69.5  319.97    69.5  385.58   69.17  387.07   69.66  411.47   69.66
  432.47   68.16  441.62   68.16  462.99   66.68     503   66.67  523.77   68.15
  641.67   68.16  662.67   69.66  687.07   69.66  689.05      69  797.09   69.02
 1007.57    69.6 1053.46   69.05 1105.13    69.5 1166.26    69.5 1289.24      70
 1358.44      70 1391.28      67 1397.71      67 1410.88    67.5 1423.61   67.68
#Mann= 3 , 0 , 0
       0    .035       0  441.62    .018       0  523.77    .035       0
Levee=-1,411.47,69.66111,-1,662.67,69.66111,	452,	451
Bank Sta=441.62,523.77
XS Rating Curve= 0 ,0
Exp/Cntr=0.3,0.1

Type RM Length L Ch R = 1 ,5485.717,76.24,115.71,155.18
XS GIS Cut Line= 6
    1076633.8714    1572711.6137    1076829.4693    1573046.4807
    1076877.2886    1573128.5979    1077000.4639    1573142.8945
    1077024.3972    1573148.7063    1077441.3814    1573888.4828
#Sta/Elev= 27
       0      69   78.73      69  109.78   68.74  165.32    68.5  234.63    68.5
  285.26   68.95  386.39      69  387.88   69.49  412.29    69.5  433.31      68
  524.83   68.04  545.84   66.59  585.84   66.59  606.84   68.09  700.97   68.14
  721.98   69.64  746.38   69.64   748.3      69  878.64      69 1030.75   69.47
 1141.26    69.5 1154.45   69.38 1175.95    69.5 1243.88    69.5 1361.64      70
 1473.37      70 1480.66   69.59
#Mann= 3 , 0 , 0
       0    .035       0  524.83    .018       0  606.84    .035       0
Levee=-1,412.22,69.49551,-1,721.97,69.6356,	452,	451
Bank Sta=524.83,606.84
XS Rating Curve= 0 ,0
Exp/Cntr=0.3,0.1

Type RM Length L Ch R = 1 ,5370.008,86.03,126.37,166.7
XS GIS Cut Line= 5
     1076613.763    1572720.0804    1076806.3819    1573058.7514
    1076892.0198    1573200.3694    1076955.7618    1573319.1616
    1077329.1978    1573958.3329
#Sta/Elev= 30
       0      69   70.07      69  134.95    68.5  246.67    68.5   278.2   68.77
  339.58      69  388.22      69   389.6   69.46  414.06   69.46   435.1   67.96
  555.11   67.97  576.15   66.48  616.17   66.48  637.12   67.97  644.56   67.97
  665.56   69.47  689.96   69.48  692.77   68.54  832.05      69  923.53      69
 1167.81    69.5 1282.43    69.5    1345   69.89 1380.07   69.38 1392.19    69.5
  1403.4      69 1409.36    68.5 1420.71      67 1428.75      67 1430.19   67.18
#Mann= 3 , 0 , 0
       0    .035       0  555.11    .018       0  637.12    .035       0
Levee=-1,414.06,69.46284,-1,665.53,69.47281,	452,	451
Bank Sta=555.11,637.12
XS Rating Curve= 0 ,0
Exp/Cntr=0.3,0.1

Type RM Length L Ch R = 1 ,5243.642,108.46,72.2,35.89
XS GIS Cut Line= 6
     1076564.143    1572746.4171    1076778.2474    1573072.9603
    1076830.8435    1573143.9279     1076774.338    1573249.5473
    1076768.6134    1573268.3881    1077229.6243    1574017.6896
#Sta/Elev= 30
       0      69   75.71   68.83  113.77    68.5  271.05    68.5  351.71      69
  389.21      69  390.48   69.42  415.29   69.43  436.62   67.93  516.59   67.86
  537.59   66.36  577.59   66.36  598.59   67.83  700.27   67.82  721.48   69.33
  746.11   69.33  748.58   68.52  949.16      69 1035.06      69 1200.76    69.5
  1335.4    69.5 1363.58    68.5 1373.54   66.44 1376.29      66 1387.57      66
 1407.17    68.5 1416.93   69.25 1432.21      70 1468.98    69.5 1498.05    69.5
#Mann= 3 , 0 , 0
       0    .035       0  516.59    .018       0  598.59    .035       0
Levee=-1,415.26,69.4268,-1,721.41,69.32336,	452,	451
Bank Sta=516.59,598.59
XS Rating Curve= 0 ,0
Exp/Cntr=0.3,0.1

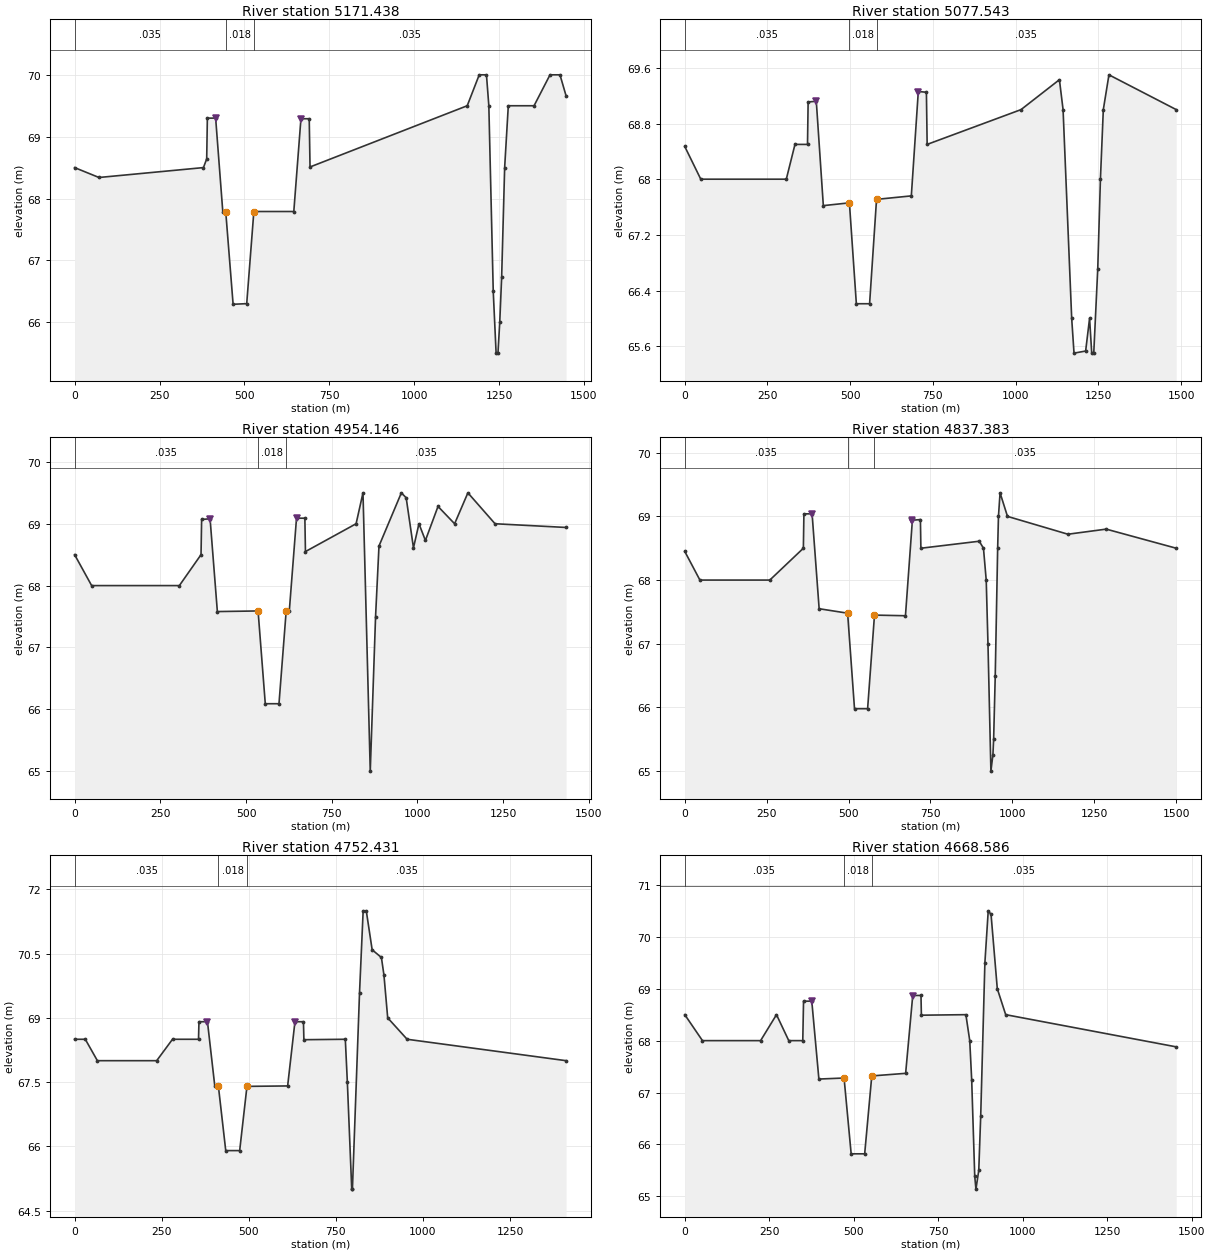
Type RM Length L Ch R = 1 ,5171.438,129.85,93.89,58
XS GIS Cut Line= 4
    1076473.9728    1572787.0572     1076687.982     1573114.152
    1076802.7586    1573391.3524    1077173.7442    1574050.7097
#Sta/Elev= 30
       0    68.5   71.73   68.34  379.43    68.5     389   68.64  390.96    69.3
  415.36    69.3  436.36   67.79  445.03   67.79  466.78   66.29  506.85    66.3
  527.88   67.79  645.56   67.79  666.56   69.29  690.96   69.29  693.32   68.51
  1156.3    69.5 1191.62      70 1212.95      70 1219.94    69.5 1232.91    66.5
 1241.35    65.5 1246.81    65.5 1252.08      66 1257.68   66.73 1266.53    68.5
 1277.26    69.5 1353.11    69.5 1400.12      70 1429.45      70 1447.47   69.66
#Mann= 3 , 0 , 0
       0    .035       0  445.03    .018       0  527.88    .035       0
Levee=-1,415.32,69.29516,-1,666.51,69.28971,	452,	451
Bank Sta=445.03,527.88
XS Rating Curve= 0 ,0
Exp/Cntr=0.3,0.1

Type RM Length L Ch R = 1 ,5077.543,83.32,123.4,163.47
XS GIS Cut Line= 6
    1076382.5326    1572832.7773     1076594.623    1573246.7981
       1076703.8    1573280.6628    1076735.5933    1573293.7882
    1076769.4509    1573405.0022    1077115.3241    1574076.1098
#Sta/Elev= 30
       0   68.47   48.38      68  306.81      68  333.04    68.5  370.91    68.5
  372.77   69.11  397.46   69.12   418.7   67.62   497.5   67.66   518.5   66.21
   558.5   66.21   579.5   67.71  684.61   67.76  705.68   69.26  730.17   69.25
  732.43    68.5  1016.1      69 1132.12   69.43 1143.16      69 1169.19      66
 1176.23    65.5 1211.36   65.53 1223.25      66 1229.74    65.5 1235.88    65.5
 1247.92   66.71 1256.03      68 1264.77      69 1281.78    69.5 1485.14      69
#Mann= 3 , 0 , 0
       0    .035       0   497.5    .018       0   579.5    .035       0
Levee=-1,397.43,69.11753,-1,705.67,69.25622,	452,	451
Bank Sta=497.5,579.5
XS Rating Curve= 0 ,0
Exp/Cntr=0.3,0.1

Type RM Length L Ch R = 1 ,4954.146,77.69,116.76,155.84
XS GIS Cut Line= 5
    1076360.9426    1572840.3973    1076522.6273    1573173.6284
     1076571.763    1573278.5482     1076625.239    1573456.0351
    1076993.4038    1574123.0998
#Sta/Elev= 30
       0    68.5   49.67      68  305.51      68  368.72    68.5  370.46   69.07
  395.13   69.08  416.36   67.58  535.11   67.59  556.13   66.09   596.1   66.09
  617.11   67.59  626.21   67.59  647.21   69.09  671.61   69.09  673.27   68.55
  821.02      69  841.11    69.5  862.31      65  877.82    67.5  887.79   68.64
  953.05    69.5  967.09   69.42  988.36   68.61 1004.36      69  1023.2   68.73
 1059.94   69.28 1108.36      69  1147.1    69.5 1226.28      69 1433.53   68.94
#Mann= 3 , 0 , 0
       0    .035       0  535.11    .018       0  617.11    .035       0
Levee=-1,395.07,69.07672,-1,647.21,69.09056,	452,	451
Bank Sta=535.11,617.11
XS Rating Curve= 0 ,0
Exp/Cntr=0.3,0.1

Type RM Length L Ch R = 1 ,4837.383,120.75,84.95,49.15
XS GIS Cut Line= 6
    1076334.2725    1572855.6373    1076541.2829    1573265.8481
    1076467.9322    1573360.2821    1076457.4628    1573380.1484
    1076496.7003    1573491.0702    1076901.9637    1574158.6599
#Sta/Elev= 30
       0   68.45   46.23      68  259.58      68  362.04    68.5  363.67   69.04
  388.67   69.04  410.18   67.55  497.12   67.48  518.12   65.98  558.12   65.98
  579.12   67.45  673.65   67.44  694.77   68.94  719.31   68.95  720.72    68.5
  898.87   68.61  911.77    68.5  920.16      68   925.5      67  934.48      65
  940.63   65.26  942.79    65.5  947.72    66.5  955.09    68.5  957.53      69
  962.43   69.37  985.08      69 1169.55   68.72 1286.43    68.8  1500.2    68.5
#Mann= 3 , 0 , 0
       0    .035       0  497.12    .018       0  579.12    .035       0
Levee=-1,388.6,69.04321,-1,694.69,68.93905,	452,	451
Bank Sta=497.12,579.12
XS Rating Curve= 0 ,0
Exp/Cntr=0.3,0.1

Type RM Length L Ch R = 1 ,4752.431,119.7,83.84,48
XS GIS Cut Line= 4
    1076284.7424    1572867.0673    1076395.3011    1573206.4879
    1076458.6237    1573499.6809    1076674.6332      1574222.16
#Sta/Elev= 30
       0    68.5   30.64    68.5   65.37      68  235.65      68  281.05    68.5
  355.73    68.5     357   68.91   381.4   68.91   402.4   67.41  412.68   67.41
  433.88    65.9  473.88    65.9   494.8    67.4  611.59   67.41  632.59   68.91
  656.99   68.91  658.24   68.49  777.15    68.5  783.01    67.5  795.58      65
  797.57      65  817.95   69.58   828.4    71.5  837.36    71.5  854.22   70.59
   880.8   70.41  888.07      70  898.85      69  954.63    68.5 1411.01      68
#Mann= 3 , 0 , 0
       0    .035       0  412.68    .018       0   494.8    .035       0
Levee=-1,381.33,68.90533,-1,632.53,68.90067,	452,	451
Bank Sta=412.68,494.8
XS Rating Curve= 0 ,0
Exp/Cntr=0.3,0.1

Type RM Length L Ch R = 1 ,4668.586,89.24,129.19,169.14
XS GIS Cut Line= 6
    1076226.3223    1572879.7674    1076292.3624    1573319.1882
    1076388.8975    1573369.8806    1076405.3927    1573385.2284
    1076423.1416    1573506.9892    1076606.0531    1574239.9401
#Sta/Elev= 30
       0    68.5   52.38      68  224.41      68  271.43    68.5  307.76      68
  349.22      68  351.49   68.76  375.89   68.76   396.9   67.26  471.41   67.28
  492.41   65.82  532.41   65.82  553.41   67.32  653.62   67.37  674.64   68.87
  699.07   68.87   700.2   68.49   831.9    68.5  843.31      68  849.11   67.24
  858.08   65.39  861.66   65.14  870.03    65.5  875.78   66.55  888.15    69.5
  898.03    70.5  906.37   70.43  924.85      69   949.7    68.5 1454.42   67.88
#Mann= 3 , 0 , 0
       0    .035       0  471.41    .018       0  553.41    .035       0
Levee=-1,375.89,68.75673,-1,674.56,68.86214,	452,	451
Bank Sta=471.41,553.41
XS Rating Curve= 0 ,0
Exp/Cntr=0.3,0.1

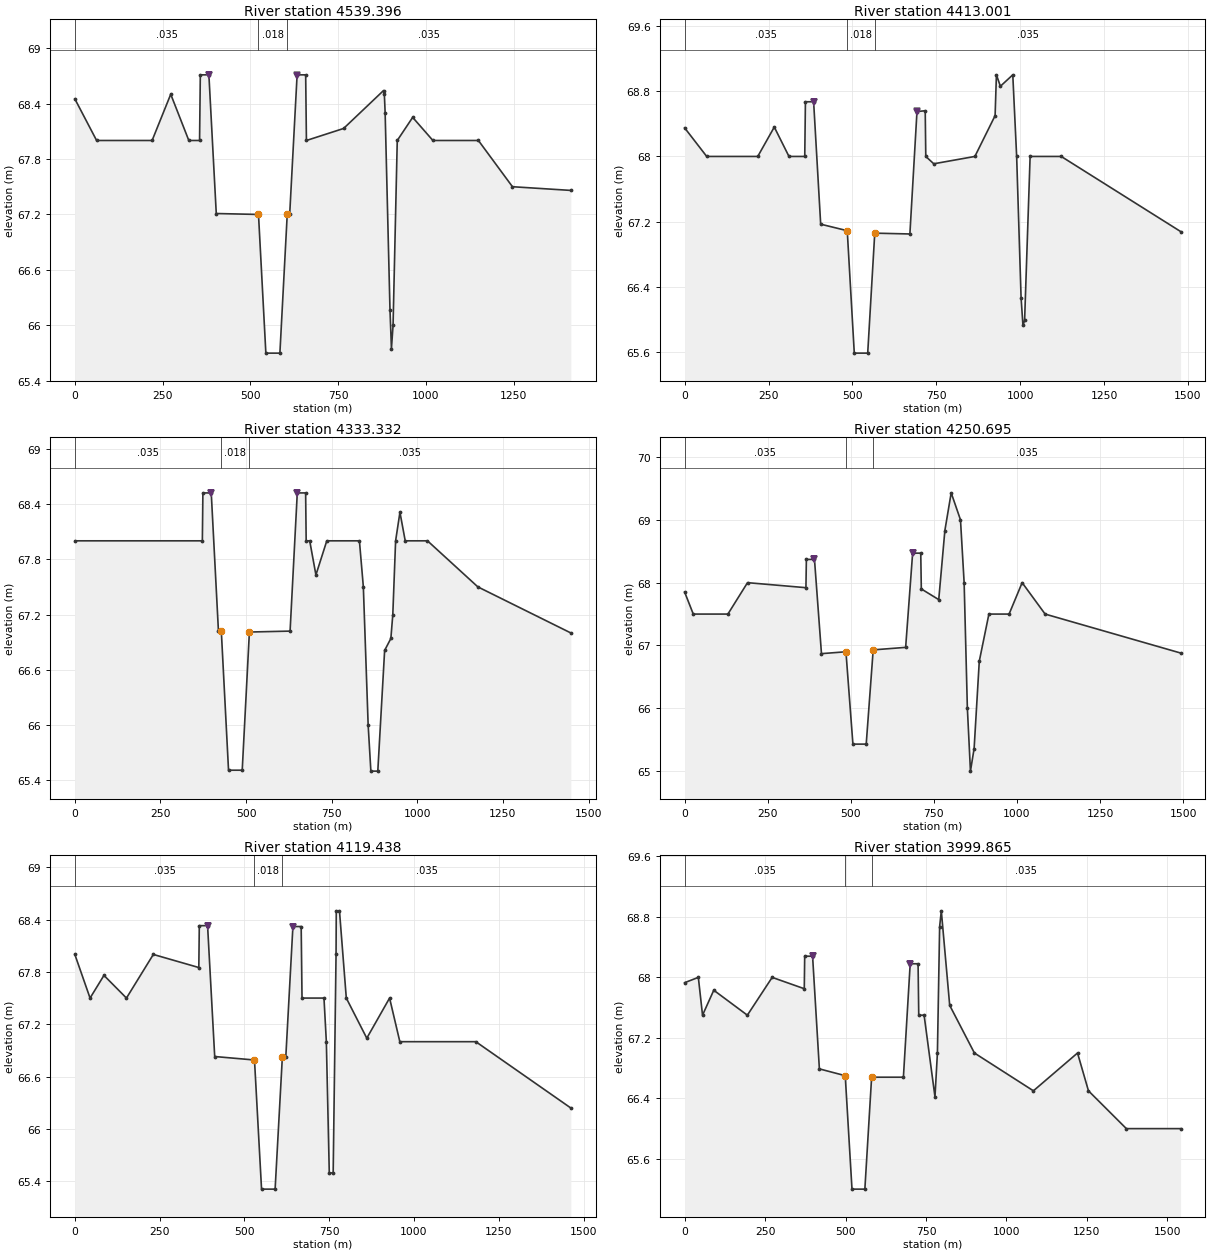
Type RM Length L Ch R = 1 ,4539.396,86.71,126.39,166.08
XS GIS Cut Line= 5
    1076190.7622    1572878.4974    1076244.4195    1573231.7166
    1076261.3718    1573396.5976    1076276.4864    1573530.0372
    1076379.9926    1574278.0402
#Sta/Elev= 30
       0   68.45   62.01      68  220.03      68   273.1    68.5   324.6      68
  355.22      68  357.35   68.71  381.76   68.71  402.76   67.21  523.02    67.2
  543.99    65.7  583.97    65.7  604.98   67.21  611.99   67.21  632.98   68.71
  657.38   68.71  659.51      68  765.37   68.13  879.05   68.54  881.45    68.5
  883.68    68.3  897.48   66.17  901.63   65.75  906.23      66   918.2      68
  962.09   68.25 1019.72      68  1149.3      68 1246.26    67.5 1412.45   67.46
#Mann= 3 , 0 , 0
       0    .035       0  523.02    .018       0  604.98    .035       0
Levee=-1,381.76,68.71023,-1,632.92,68.70223,	452,	451
Bank Sta=523.02,604.98
XS Rating Curve= 0 ,0
Exp/Cntr=0.3,0.1

Type RM Length L Ch R = 1 ,4413.001,115.26,79.67,44.08
XS GIS Cut Line= 6
    1076164.0922    1572878.4974    1076209.2256     1573235.565
    1076222.5123    1573322.9982    1076133.2626    1573400.5867
    1076117.1021    1573413.1684    1076256.8024    1574293.2802
#Sta/Elev= 30
       0   68.35   65.75      68   217.9      68  267.17   68.36  310.94      68
  357.98      68  359.98   68.67  384.41   68.67  405.44   67.17  484.61   67.09
  505.61   65.59  545.61   65.59  566.61   67.06  671.33   67.05  692.46   68.55
  717.02   68.56   718.7      68   742.5   67.91  865.02      68  925.31    68.5
  929.22      69  941.06   68.86     978      69  989.52      68 1002.71   66.27
 1008.28   65.93 1013.23   65.99 1029.66      68  1122.4      68 1478.21   67.08
#Mann= 3 , 0 , 0
       0    .035       0  484.61    .018       0  566.61    .035       0
Levee=-1,384.41,68.66766,-1,692.46,68.55412,	452,	451
Bank Sta=484.61,566.61
XS Rating Curve= 0 ,0
Exp/Cntr=0.3,0.1

Type RM Length L Ch R = 1 ,4333.332,118.69,82.64,46.58
XS GIS Cut Line= 5
     1076073.922    1572869.6073    1076095.7669    1573242.7902
    1076095.8113    1573296.6783    1076098.9794    1573542.8593
    1076206.0023    1574309.7902
#Sta/Elev= 30
       0      68  372.35      68  373.92   68.52  398.33   68.52  419.33   67.02
  427.71   67.02  448.79   65.51  488.77   65.51   509.7   67.01  628.54   67.02
  649.54   68.52  673.94   68.52   675.5      68  685.83      68  703.97   67.63
  735.73      68  830.98      68  842.46    67.5   856.5      66  864.43    65.5
  884.68    65.5   904.6   66.81  922.82   66.94  928.48    67.2  936.67      68
  949.31   68.31  964.73      68 1029.76      68 1176.82    67.5 1448.27      67
#Mann= 3 , 0 , 0
       0    .035       0  427.71    .018       0   509.7    .035       0
Levee=-1,398.26,68.52103,-1,649.51,68.51373,	452,	451
Bank Sta=427.71,509.7
XS Rating Curve= 0 ,0
Exp/Cntr=0.3,0.1

Type RM Length L Ch R = 1 ,4250.695,91.93,131.26,170.59
XS GIS Cut Line= 6
    1075988.8318    1572875.9574    1075976.0759    1573241.9826
    1075969.7818    1573329.3483    1076058.1338    1573400.5828
    1076052.2987    1573543.5784    1076155.2022    1574318.6802
#Sta/Elev= 30
       0   67.85   25.95    67.5  130.16    67.5  189.18      68  364.95   67.92
  366.28   68.37  390.69   68.37   411.7   66.87  485.33    66.9  506.33   65.43
  546.33   65.43  567.33   66.93  664.99   66.97     686   68.47  710.43   68.47
  712.14    67.9  764.57   67.73  783.01   68.83  802.02   69.43  829.98      69
  840.97      68  850.71      66  859.99      65  871.02   65.36  886.55   66.75
   915.5    67.5  976.22    67.5 1015.52      68 1084.66    67.5 1492.35   66.88
#Mann= 3 , 0 , 0
       0    .035       0  485.33    .018       0  567.33    .035       0
Levee=-1,390.63,68.36917,-1,686.03,68.46698,	452,	451
Bank Sta=485.33,567.33
XS Rating Curve= 0 ,0
Exp/Cntr=0.3,0.1

Type RM Length L Ch R = 1 ,4119.438,81.06,119.57,158.08
XS GIS Cut Line= 6
    1075939.3017    1572873.4173    1075944.9918     1573240.313
    1075935.4917    1573345.8583     1075925.201     1573401.759
    1075915.9794    1573539.0491    1075936.7617    1574333.9203
#Sta/Elev= 30
       0      68   44.88    67.5   85.85   67.76   152.2    67.5  231.42      68
  365.57   67.85  367.01   68.33  391.42   68.33  412.42   66.83  529.75   66.79
  550.55   65.31  590.57   65.31  611.84   66.82  622.02   66.82  643.02   68.32
  667.42   68.32  669.89    67.5  734.65    67.5  741.62      67  750.32   65.49
  761.78    65.5  770.24      68  770.91    68.5  780.32    68.5  800.46    67.5
  860.88   67.04  928.08    67.5  958.33      67 1182.36      67 1462.49   66.24
#Mann= 3 , 0 , 0
       0    .035       0  529.75    .018       0  611.84    .035       0
Levee=-1,391.34,68.32964,-1,642.95,68.31426,	452,	451
Bank Sta=529.75,611.84
XS Rating Curve= 0 ,0
Exp/Cntr=0.3,0.1

Type RM Length L Ch R = 1 ,3999.865,97.98,65.86,33.74
XS GIS Cut Line= 6
    1075901.2017    1572864.5273    1075907.5517    1573321.7282
    1075803.0057    1573387.9396    1075791.9814    1573394.7534
     1075786.682    1573526.0121    1075825.0015    1574340.9053
#Sta/Elev= 30
       0   67.93   42.55      68   55.58    67.5   90.49   67.83  194.85    67.5
  271.96      68  371.73   67.85  373.03   68.28  397.55   68.28  418.66   66.79
  498.99    66.7  519.99    65.2  559.99    65.2  580.99   66.68  679.75   66.68
  700.84   68.18  725.34   68.18  727.42    67.5  744.08    67.5  777.85   66.42
  785.42      67  792.32   68.67   797.5   68.88  823.59   67.63  900.37      67
 1083.71    66.5 1220.78      67 1254.75    66.5 1372.53      66 1541.11      66
#Mann= 3 , 0 , 0
       0    .035       0  498.99    .018       0  580.99    .035       0
Levee=-1,397.48,68.2845,-1,700.83,68.17663,	452,	451
Bank Sta=498.99,580.99
XS Rating Curve= 0 ,0
Exp/Cntr=0.3,0.1

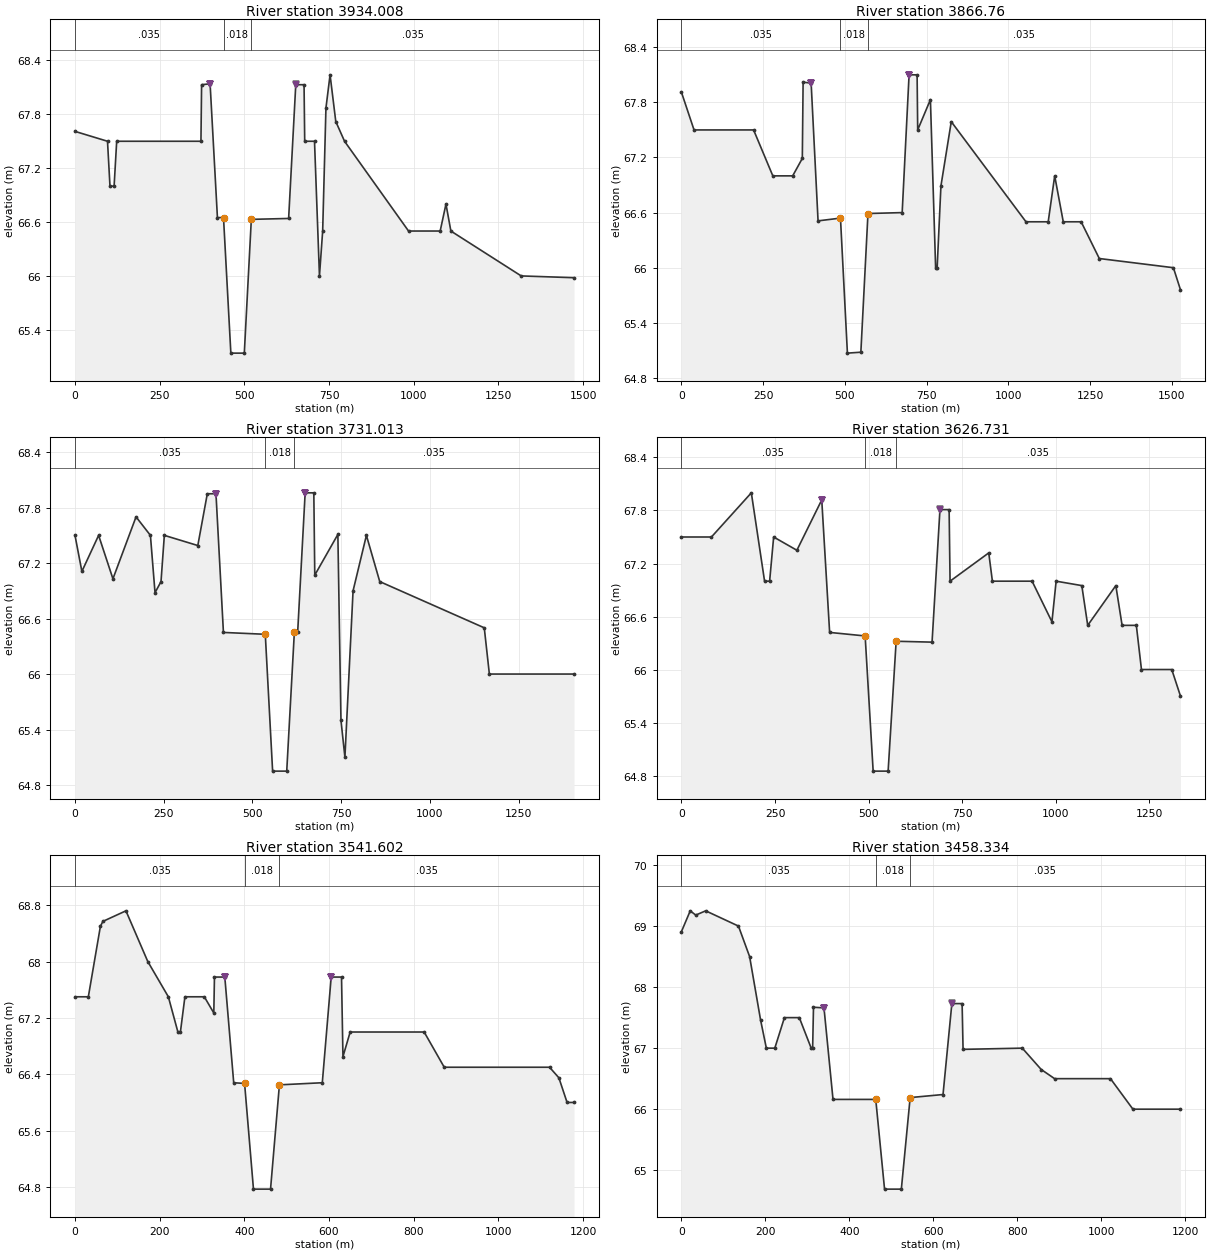
Type RM Length L Ch R = 1 ,3934.008,108.06,67.25,26.76
XS GIS Cut Line= 5
    1075804.4698    1572849.9223    1075789.6089    1573223.3002
    1075795.2326    1573287.7291    1075742.7034    1573519.6107
    1075743.5097    1574316.3519
#Sta/Elev= 30
       0   67.61   95.96    67.5  103.26      67  115.46      67  123.08    67.5
  371.76    67.5  373.67   68.13  398.79   68.14  420.41   66.65  438.35   66.65
  460.03   65.14  499.76   65.14  520.46   66.63  630.59   66.64  651.64   68.13
   676.1   68.13  678.02    67.5  706.95    67.5  721.56      66  731.03    66.5
   740.7   67.87  752.87   68.24  769.74   67.72   795.6    67.5  984.51    66.5
 1077.86    66.5 1094.95    66.8 1109.44    66.5 1316.99      66 1472.85   65.98
#Mann= 3 , 0 , 0
       0    .035       0  438.35    .018       0  520.46    .035       0
Levee=-1,398.75,68.13966,-1,651.64,68.13318,	452,	451
Bank Sta=438.35,520.46
XS Rating Curve= 0 ,0
Exp/Cntr=0.3,0.1

Type RM Length L Ch R = 1 ,3866.76 ,97.63,135.75,173.54
XS GIS Cut Line= 6
     1075756.633    1572841.4556    1075690.9219    1573207.6782
    1075669.0029    1573284.6865     1075751.079    1573369.0688
    1075711.3641    1573514.6497    1075685.5129    1574319.7386
#Sta/Elev= 30
       0   67.91   38.47    67.5  220.65    67.5  279.46      67  340.19      67
  369.66   67.19  372.07   68.02  396.65   68.01   417.8   66.51  486.35   66.54
  507.57   65.07  548.72   65.08  570.49   66.59  675.08    66.6  696.21    68.1
  720.75    68.1  722.55    67.5  761.44   67.83  777.38      66  782.08      66
  793.63   66.89  825.25   67.59 1053.72    66.5 1121.74    66.5 1141.59      67
 1167.79    66.5  1222.5    66.5 1278.02    66.1 1504.65      66 1526.26   65.76
#Mann= 3 , 0 , 0
       0    .035       0  486.35    .018       0  570.49    .035       0
Levee=-1,396.65,68.01249,-1,696.21,68.0983,	452,	451
Bank Sta=486.35,570.49
XS Rating Curve= 0 ,0
Exp/Cntr=0.3,0.1

Type RM Length L Ch R = 1 ,3731.013,59.63,104.28,148.99
XS GIS Cut Line= 5
    1075689.3229    1572830.0256     1075634.901    1573198.8102
    1075614.3722    1573360.8447    1075592.9913    1573495.9114
    1075549.9401    1574227.6634
#Sta/Elev= 30
       0    67.5   19.42   67.11   66.56    67.5   106.9   67.03  171.99    67.7
   212.5    67.5  225.47   66.88  242.34      67  251.72    67.5  346.01   67.39
  372.78   67.95  397.19   67.95   418.2   66.45  536.11   66.43  556.78   64.95
  596.55   64.95  618.12   66.46  627.46   66.46  648.46   67.96  672.86   67.96
  675.55   67.07  740.61   67.51  749.32    65.5  760.48    65.1  783.43    66.9
  821.01    67.5  858.59      67 1153.07    66.5 1167.43      66 1405.87      66
#Mann= 3 , 0 , 0
       0    .035       0  536.11    .018       0  618.12    .035       0
Levee=-1,397.19,67.95077,-1,648.45,67.95578,	452,	451
Bank Sta=536.11,618.12
XS Rating Curve= 0 ,0
Exp/Cntr=0.3,0.1

Type RM Length L Ch R = 1 ,3626.731,129.79,85.13,40.45
XS GIS Cut Line= 6
    1075627.4103    1572844.6306    1075607.1429    1573194.4161
    1075598.2002    1573311.9916    1075498.3482    1573345.6608
      1075481.36    1573355.1716    1075441.9899    1574094.3131
#Sta/Elev= 30
       0    67.5   80.12    67.5   186.7      68  222.09      67  235.59      67
  246.34    67.5  308.41   67.35  374.85   67.92  395.92   66.42  490.79   66.38
  512.21   64.85  552.21   64.85  573.66   66.32   669.6   66.31  690.69   67.81
  715.19   67.81  717.68      67  821.06   67.32  830.81      67  936.88      67
  989.92   66.54 1001.12      67  1069.7   66.95 1085.51    66.5 1160.62   66.95
 1177.38    66.5 1215.41    66.5 1229.11      66 1310.09      66 1333.33    65.7
#Mann= 3 , 0 , 0
       0    .035       0  490.79    .018       0  573.66    .035       0
Levee=-1,374.85,67.91953,-1,690.69,67.81227,	452,	451
Bank Sta=490.79,573.66
XS Rating Curve= 0 ,0
Exp/Cntr=0.3,0.1

Type RM Length L Ch R = 1 ,3541.602,126.01,83.27,40.5
XS GIS Cut Line= 5
    1075535.9701    1572849.7106    1075492.6232    1573176.2878
    1075477.1842    1573245.7481    1075441.3828     1573471.912
    1075373.4098     1574016.843
#Sta/Elev= 30
       0    67.5   31.53    67.5   60.02    68.5   65.89   68.57  120.34   68.72
  171.97      68  220.52    67.5  243.08      67  249.02      67  259.66    67.5
  305.49    67.5  327.91   67.27  329.44   67.78  353.89   67.78  374.93   66.28
   400.6   66.27  421.58   64.77  461.92   64.77  482.88   66.25  584.18   66.28
  605.18   67.78  629.58   67.78  632.97   66.65     650      67  824.78      67
   872.2    66.5 1120.97    66.5 1143.02   66.35 1162.39      66 1178.73      66
#Mann= 3 , 0 , 0
       0    .035       0   400.6    .018       0  482.88    .035       0
Levee=-1,353.89,67.78058,-1,605.18,67.77722,	452,	451
Bank Sta=400.6,482.88
XS Rating Curve= 0 ,0
Exp/Cntr=0.3,0.1

Type RM Length L Ch R = 1 ,3458.334,45.21,87.96,130.7
XS GIS Cut Line= 6
      1075468.66    1572854.7906    1075397.7402     1573161.268
    1075350.5497    1573280.2415    1075429.7808    1573344.9978
    1075402.6022    1573465.7731    1075323.8797    1573980.0129
#Sta/Elev= 30
       0   68.91   20.91   69.25   34.05   69.18   57.75   69.25  135.83      69
   162.4    68.5  188.54   67.46  202.25      67  222.42      67  245.32    67.5
  280.79    67.5   309.1      67  312.56      67  314.58   67.67  339.58   67.66
   361.1   66.16  462.89   66.16  483.89   64.69  523.89   64.69  544.89   66.19
   623.2   66.24  644.24   67.73  668.69   67.73  670.95   66.98  812.08      67
  857.18   66.65  889.04    66.5 1022.19    66.5 1075.62      66 1188.92      66
#Mann= 3 , 0 , 0
       0    .035       0  462.89    .018       0  544.89    .035       0
Levee=-1,339.58,67.66425,-1,644.24,67.73342,	452,	451
Bank Sta=462.89,544.89
XS Rating Curve= 0 ,0
Exp/Cntr=0.3,0.1

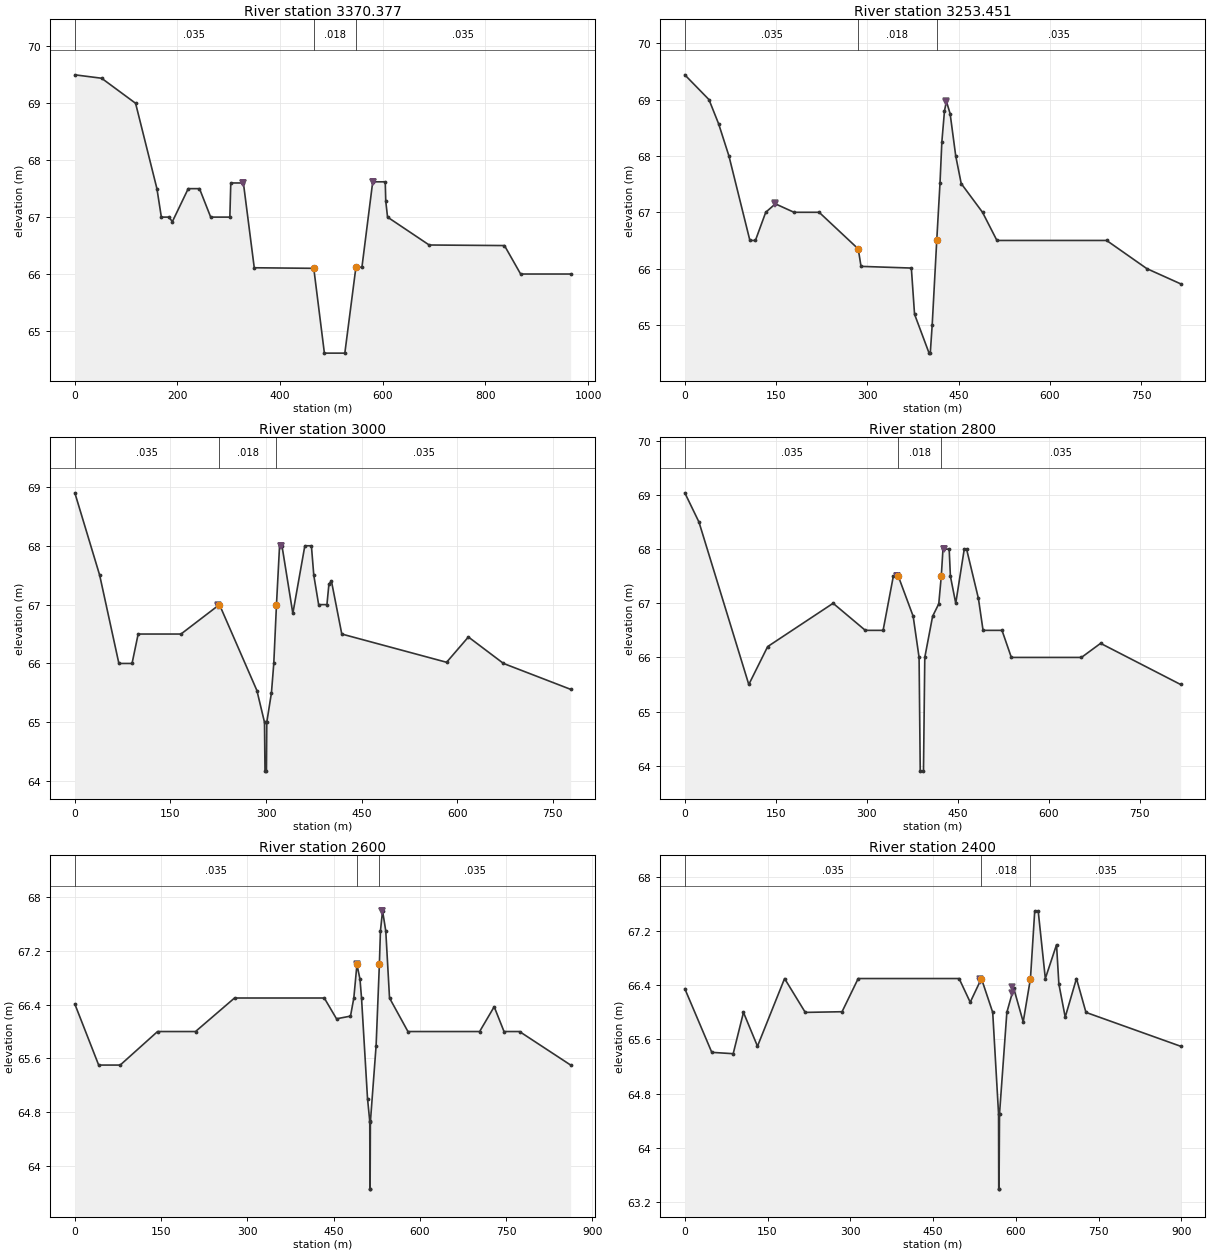
Type RM Length L Ch R = 1 ,3370.377,105.01,116.93,129.01
XS GIS Cut Line= 5
    1075430.5599    1572862.4107    1075337.9403    1573151.8017
    1075332.7697    1573282.7815    1075306.2176    1573450.5156
    1075204.4994    1573797.1325
#Sta/Elev= 27
       0    69.5   52.22   69.44  118.38      69  159.94    67.5  168.56      67
  183.23      67  190.02   66.92  220.92    67.5  242.88    67.5  264.69      67
  302.03      67  303.85    67.6  328.42    67.6  349.57   66.11  465.52    66.1
  486.21   64.61  526.04   64.61  547.63   66.12  559.36   66.12  580.36   67.62
  604.76   67.62  605.77   67.28  609.25      67  690.35   66.51  837.05    66.5
  868.54      66  965.99      66
#Mann= 3 , 0 , 0
       0    .035       0  465.52    .018       0  547.63    .035       0
Levee=-1,328.42,67.60355,-1,580.36,67.6181,	452,	451
Bank Sta=465.52,547.63
XS Rating Curve= 0 ,0
Exp/Cntr=0.3,0.1

Type RM Length L Ch R = 1 ,3253.451,270.63,253.45,287.83
BEGIN DESCRIPTION:
Natural entrega
END DESCRIPTION:
XS GIS Cut Line= 4
    1075376.9439    1572916.6924    1075314.3958    1573116.1355
    1075171.5789    1573401.7692    1075008.1404    1573637.4453
#Sta/Elev= 30
       0   69.44   39.74      69   55.61   68.57   72.54      68  107.01    66.5
  116.09    66.5  133.06      67   148.9   67.15  179.51      67  220.86      67
  285.13   66.35  289.73   66.04  372.46   66.01  377.72   65.19  401.61    64.5
  403.57    64.5  406.73      65  414.21    66.5  419.58   67.52  422.61   68.25
  426.94    68.8   430.1   68.97  436.21   68.75  445.42      68  454.43   67.51
  489.46      67  513.14    66.5  693.52    66.5   759.6      66  815.17   65.73
#Mann= 3 , 0 , 0
       0    .035       0  285.13    .018       0  414.21    .035       0
Levee=-1,148.46,67.17,-1,429.75,68.97,	452,
Bank Sta=285.13,414.21
XS Rating Curve= 0 ,0
Pilot Channel=64.5,60,0.018
Exp/Cntr=0.3,0.1

Type RM Length L Ch R = 1 ,3000    ,173.16,200,161.41
BEGIN DESCRIPTION:
Natural entrega
END DESCRIPTION:
XS GIS Cut Line= 4
    1075085.5796    1572874.2425    1075009.8838    1573116.4647
    1075027.4083    1573337.2613    1074970.9089    1573634.4449
#Sta/Elev= 30
       0    68.9   38.96    67.5   69.12      66   89.75      66   99.35    66.5
  166.51    66.5  226.86      67   285.6   65.54  297.53      65   298.3   64.17
  300.57   64.17   301.1      65  308.41    65.5  312.09      66  316.31      67
  321.15      68  324.95      68  341.98   66.85  360.81      68   371.1      68
  374.83    67.5  382.45      67  395.47      67  398.59   67.35  402.53    67.4
  418.76    66.5  583.16   66.02  617.34   66.45  672.43      66  777.77   65.56
#Mann= 3 , 0 , 0
       0    .035       0  226.86    .018       0  316.31    .035       0
Levee=-1,224.78,67,-1,322.96,68,,
Bank Sta=226.86,316.31
XS Rating Curve= 0 ,0
Pilot Channel=64.168,60,0.018
Exp/Cntr=0.3,0.1

Type RM Length L Ch R = 1 ,2800    ,229.25,200,147.14
BEGIN DESCRIPTION:
Natural entrega
END DESCRIPTION:
XS GIS Cut Line= 5
    1074975.7773    1572839.8466     1074932.279    1573199.6772
    1074894.8615    1573241.6759     1074938.394    1573378.7808
    1074939.9526    1573633.6511
#Sta/Elev= 30
       0   69.04   23.35    68.5   105.5    65.5  136.59    66.2   244.5      67
   297.6    66.5  326.92    66.5  343.78    67.5  351.98    67.5  376.49   66.76
  386.23      66  388.14   63.91   393.5    63.9  395.64      66  408.54   66.76
   418.7   66.99  422.83    67.5  425.62      68  435.84      68  437.88    67.5
  446.68      67  460.71      68  464.56      68  484.04   67.09  491.71    66.5
  522.95    66.5  538.33      66  653.93      66  685.49   66.26  817.42    65.5
#Mann= 3 , 0 , 0
       0    .035       0  351.98    .018       0  422.83    .035       0
Levee=-1,350.45,67.5,-1,426.53,68,,
Bank Sta=351.98,422.83
XS Rating Curve= 0 ,0
Pilot Channel=63.906,60,0.018
Exp/Cntr=0.3,0.1

Type RM Length L Ch R = 1 ,2600    ,152.29,200,272.51
BEGIN DESCRIPTION:
Natural entrega
END DESCRIPTION:
XS GIS Cut Line= 5
     1074802.369    1572827.1995     1074795.417    1573204.1704
    1074850.8937    1573309.4669    1074889.7875    1573309.4669
    1074915.3463    1573636.0324
#Sta/Elev= 30
       0   66.41   41.48    65.5   78.92    65.5  143.92      66  209.92      66
  277.81    66.5  433.93    66.5  455.21   66.19  479.54   66.23  485.32    66.5
  490.75      67  496.05   66.78  498.73    66.5  509.15      65  513.06   64.66
  513.38   63.65  513.66   63.65  514.13   64.65  524.09   65.79  529.76      67
  531.63    67.5  535.31    67.8  540.91    67.5  547.43    66.5  579.46      66
  704.18      66  729.49   66.37   746.6      66  773.56      66  862.51    65.5
#Mann= 3 , 0 , 0
       0    .035       0  490.75    .018       0  529.76    .035       0
Levee=-1,490.79,67,-1,535.19,67.8,,
Bank Sta=490.75,529.76
XS Rating Curve= 0 ,0
Pilot Channel=63.644,60,0.018
Exp/Cntr=0.3,0.1

Type RM Length L Ch R = 1 ,2400    ,201.37,200,132.8
BEGIN DESCRIPTION:
Natural entrega
END DESCRIPTION:
XS GIS Cut Line= 6
    1074705.0021    1572829.3162    1074705.5453     1573245.692
    1074757.8285    1573373.6044    1074786.6337    1573352.2546
     1074828.845    1573423.1331    1074885.9775    1573641.5886
#Sta/Elev= 30
       0   66.35   48.93   65.41   87.71   65.39  106.33      66  131.74    65.5
  180.84    66.5  218.35      66  285.04   66.01  314.27    66.5  497.17    66.5
  517.33   66.15  537.63    66.5   558.1      66  568.71    64.5  569.03   63.39
  569.56   63.39  570.43    64.5  583.73      66  596.04   66.36  613.38   65.86
  626.52    66.5  634.28    67.5  640.51    67.5  653.48    66.5  673.79      67
  678.01   66.42  689.52   65.93  709.92    66.5  727.14      66  898.71    65.5
#Mann= 3 , 0 , 0
       0    .035       0  537.63    .018       0  626.52    .035       0
Levee=-1,535.81,66.5,-1,593.64,66.37,,
Bank Sta=537.63,626.52
XS Rating Curve= 0 ,0
Pilot Channel=63.382,60,0.018
Exp/Cntr=0.3,0.1