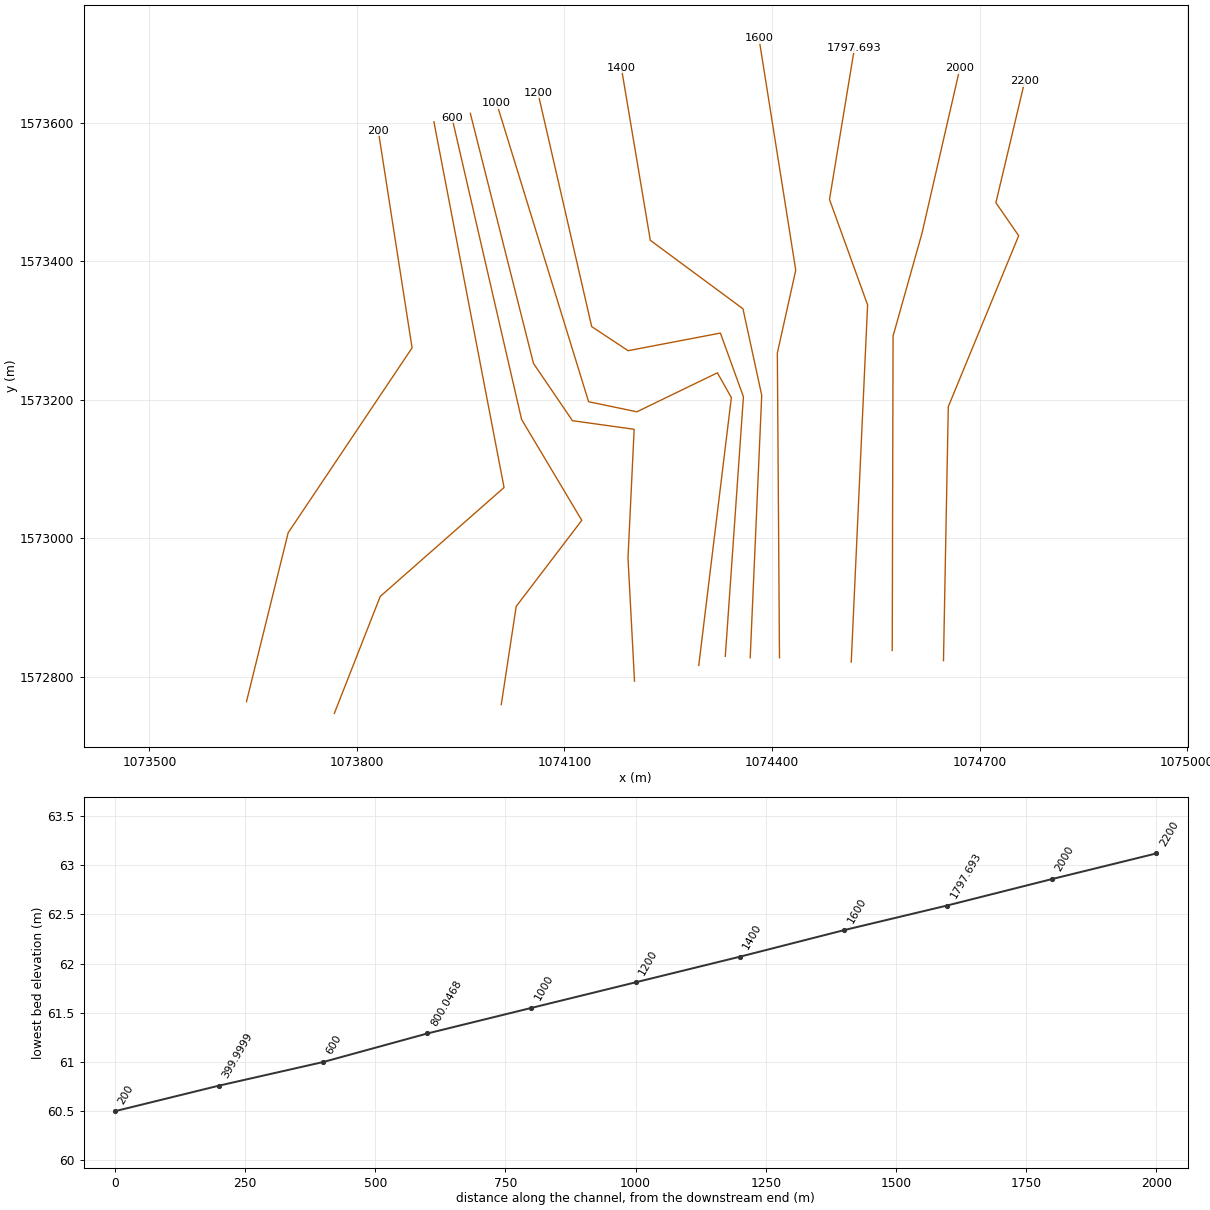
HEC-RAS study HECRAS_v2.prj: HECRAS_v2

--- HECRAS_v2.g01 (geometry) --- (continued)

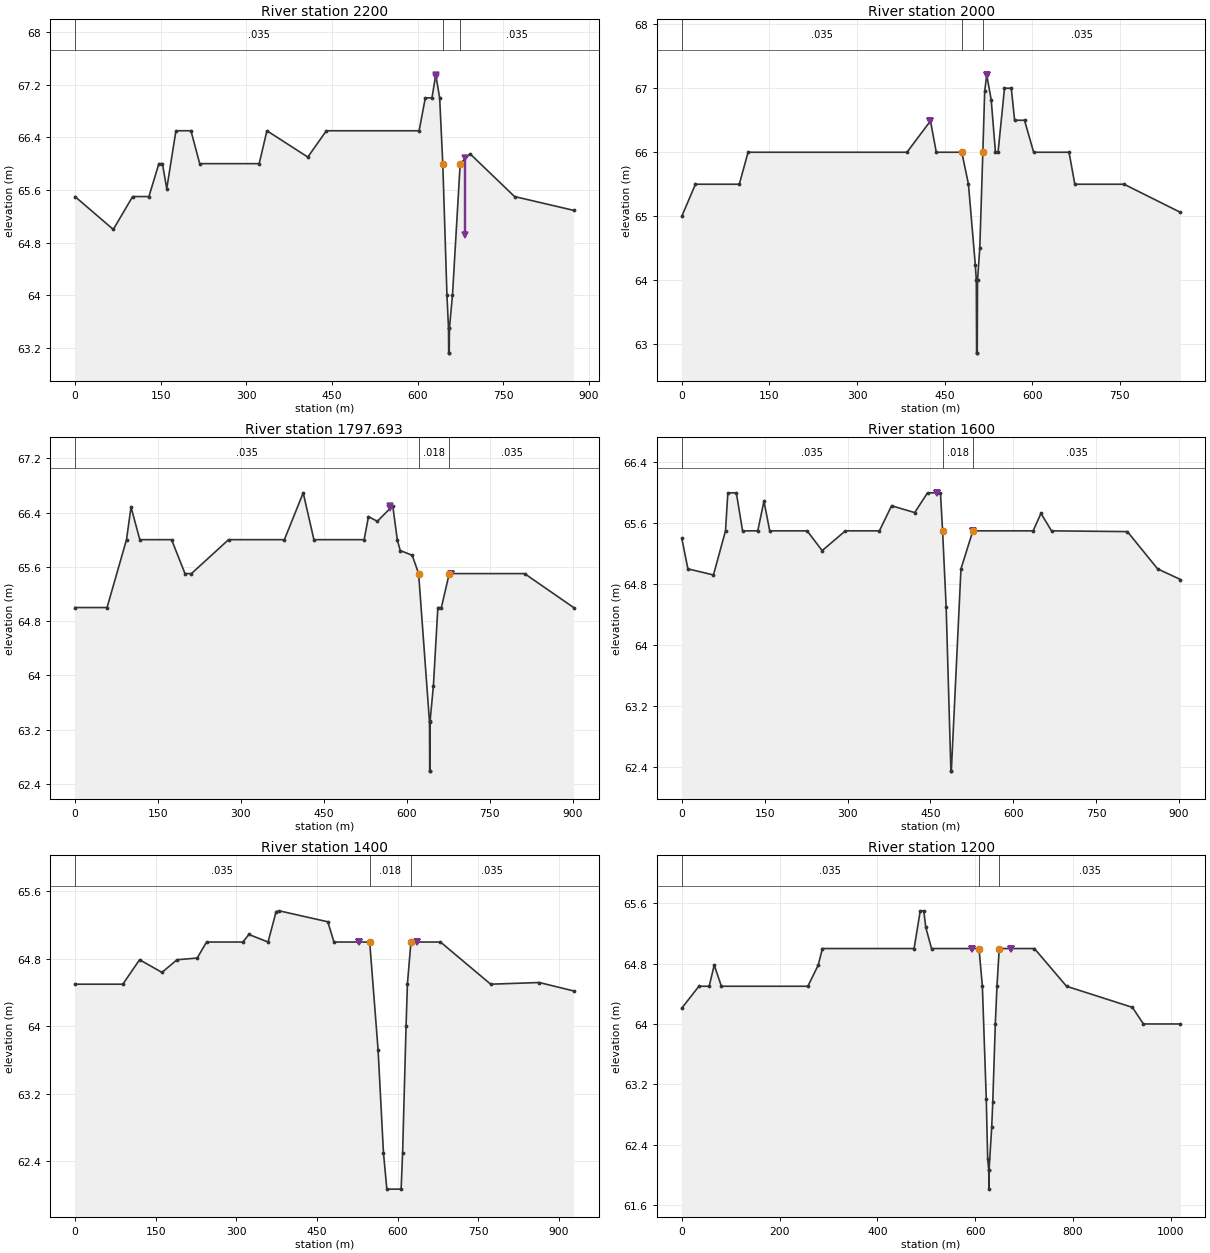
Type RM Length L Ch R = 1 ,2200    ,210.95,200,171.25
BEGIN DESCRIPTION:
Natural entrega
END DESCRIPTION:
XS GIS Cut Line= 5
     1074647.852    1572822.9662    1074654.8093    1573190.1452
    1074756.5623    1573437.2428    1074723.6121    1573484.9154
    1074765.3273    1573660.6387
#Sta/Elev= 30
       0    65.5   67.08      65  100.97    65.5  129.45    65.5  146.89      66
  153.11      66  160.67   65.62  176.74    66.5  203.04    66.5  218.36      66
  322.49      66  336.06    66.5  407.64    66.1  440.13    66.5   602.5    66.5
  613.36      67  625.02      67  631.62   67.35  638.46      67  643.93      66
  651.23      64  653.95    63.5  654.28   63.12  655.19   63.12  655.57    63.5
  660.89      64  674.39      66  691.66   66.15  769.56    65.5  873.03   65.29
#Mann= 3 , 0 , 0
       0    .035       0  643.93    .018       0  674.39    .035       0
Levee=-1,632.24,67.35,-1,683.69,64.92,,
Bank Sta=643.93,674.39
XS Rating Curve= 0 ,0
Pilot Channel=63.12,60,0.018
Exp/Cntr=0.3,0.1

Type RM Length L Ch R = 1 ,2000    ,178.48,202.31,216.87
BEGIN DESCRIPTION:
Natural entrega
END DESCRIPTION:
XS GIS Cut Line= 4
    1074573.7685    1572837.7829    1074574.9818    1573292.1952
    1074616.7788    1573440.8024    1074671.6646    1573679.6887
#Sta/Elev= 30
       0      65   23.35    65.5   98.44    65.5  113.46      66  385.56      66
  425.81   66.49  435.77      66   479.4      66  490.84    65.5  502.56   64.24
  504.29      64  504.81   62.86  505.85   62.86  506.36      64  510.23    64.5
  515.48      66  518.62   66.95  522.13   67.21  529.78   66.82  537.07      66
  541.51      66  552.55      67  564.19      67  569.89    66.5  586.83    66.5
  602.47      66  663.08      66  672.95    65.5  757.28    65.5   853.9   65.06
#Mann= 3 , 0 , 0
       0    .035       0   479.4    .018       0  515.48    .035       0
Levee=-1,425.24,66.49,-1,522.07,67.21,,
Bank Sta=479.4,515.48
XS Rating Curve= 0 ,0
Pilot Channel=62.858,60,0.018
Exp/Cntr=0.3,0.1

Type RM Length L Ch R = 1 ,1797.693,214.45,197.69,185.65
BEGIN DESCRIPTION:
Natural entrega
END DESCRIPTION:
XS GIS Cut Line= 4
    1074514.5018    1572820.8495    1074538.1554    1573337.1533
    1074483.0853    1573489.6785    1074519.2643    1573709.0575
#Sta/Elev= 30
       0      65   57.98      65   93.14      66  101.31   66.48  117.22      66
   174.6      66  198.88    65.5   210.5    65.5  277.59      66  378.51      66
  412.53   66.69   431.9      66  522.64      66  530.54   66.34   546.5   66.27
  574.38    66.5  582.77   65.99  587.92   65.84  609.49   65.77  621.15    65.5
  640.84   63.31   641.2   62.59  641.36   62.59   641.9   63.33  647.87   63.85
  655.91      65  662.28      65  676.48    65.5  812.64    65.5  901.35      65
#Mann= 3 , 0 , 0
       0    .035       0  621.15    .018       0  676.48    .035       0
Levee=-1,569.98,66.5,-1,679.12,65.5,,
Bank Sta=621.15,676.48
XS Rating Curve= 0 ,0
Pilot Channel=62.593,60,0.018
Exp/Cntr=0.3,0.1

Type RM Length L Ch R = 1 ,1600    ,134.48,200,216.46
BEGIN DESCRIPTION:
Natural entrega
END DESCRIPTION:
XS GIS Cut Line= 4
    1074410.7849    1572827.1995    1074407.7038    1573267.6814
     1074434.311    1573387.4131    1074381.1515    1573722.5513
#Sta/Elev= 30
       0    65.4   11.05      65   57.27   64.92   79.08    65.5   83.31      66
   98.66      66  109.99    65.5  137.43    65.5  148.67   65.89  159.11    65.5
  226.78    65.5  254.02   65.24  296.01    65.5  357.63    65.5  379.63   65.83
  421.45   65.74  444.65      66  468.11      66  471.94    65.5   478.4    64.5
  486.99   62.34  487.76   62.34   505.2      65  526.76    65.5  635.79    65.5
  649.99   65.73  669.06    65.5  806.39   65.49  861.06      65  902.47   64.86
#Mann= 3 , 0 , 0
       0    .035       0  471.94    .018       0  526.76    .035       0
Levee=-1,462.1,66,-1,527.73,65.5,,
Bank Sta=471.94,526.76
XS Rating Curve= 0 ,0
Pilot Channel=62.334,60,0.018
Exp/Cntr=0.3,0.1

Type RM Length L Ch R = 1 ,1400    ,66.77,200,200.75
BEGIN DESCRIPTION:
Natural entrega
END DESCRIPTION:
XS GIS Cut Line= 5
    1074368.4515    1572827.1995    1074385.1202    1573206.6128
    1074357.9785    1573331.6301    1074224.0756    1573430.5995
    1074182.1844    1573680.2179
#Sta/Elev= 27
       0    64.5   88.97    64.5  120.09   64.79  161.81   64.64  189.73   64.79
   227.3   64.81  244.67      65  312.31      65  323.28   65.09  359.04      65
  374.04   65.36  379.78   65.37  470.21   65.24   481.6      65  548.07      65
  563.68   63.72  573.67    62.5  579.96   62.07   606.5   62.07  609.26    62.5
  615.68      64  618.19    64.5  624.74      65  679.73      65  773.02    64.5
  863.42   64.52  927.33   64.42
#Mann= 3 , 0 , 0
       0    .035       0  548.07    .018       0  624.74    .035       0
Levee=-1,527.81,65,-1,636.78,65,,
Bank Sta=548.07,624.74
XS Rating Curve= 0 ,0
Pilot Channel=62.072,60,0.018
Exp/Cntr=0.3,0.1

Type RM Length L Ch R = 1 ,1200    ,254.92,200,253.54
BEGIN DESCRIPTION:
Natural entrega
END DESCRIPTION:
XS GIS Cut Line= 6
    1074332.4681    1572829.3162    1074358.6619    1573204.4961
    1074325.3532    1573296.4952    1074191.9693    1573271.0397
    1074139.3303     1573305.863    1074061.5342    1573644.2345
#Sta/Elev= 30
       0   64.21   34.97    64.5   55.95    64.5   66.32   64.78      81    64.5
  257.81    64.5  279.04   64.78  287.64      65  475.11      65  487.74    65.5
  494.99    65.5  499.05   65.28  510.83      65  607.92      65   614.8    64.5
  622.81      63  625.67   62.21  627.91   62.06   628.2   61.81  628.45   62.06
  633.89   62.63  636.05   62.96  641.27      64  644.66    64.5  649.32      65
  721.23      65  786.94    64.5  921.72   64.22  944.22      64 1020.04      64
#Mann= 3 , 0 , 0
       0    .035       0  607.92    .018       0  649.32    .035       0
Levee=-1,594.55,65,-1,672.87,65,,
Bank Sta=607.92,649.32
XS Rating Curve= 0 ,0
Pilot Channel=61.81,60,0.018
Exp/Cntr=0.3,0.1

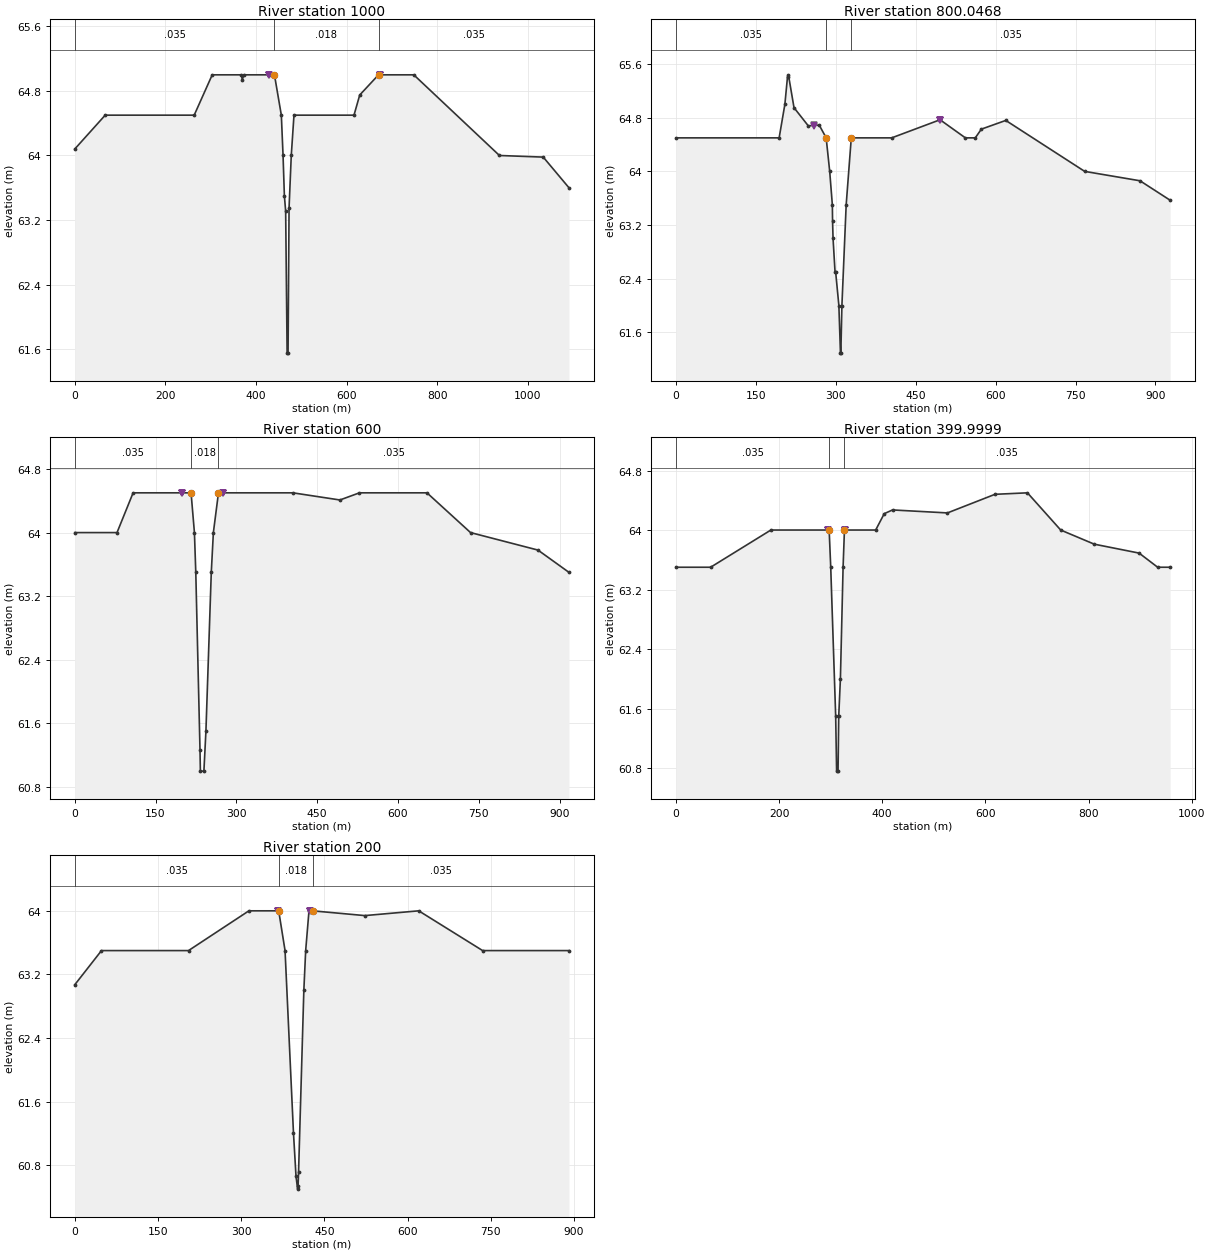
Type RM Length L Ch R = 1 ,1000    ,294.09,199.95,86.36
BEGIN DESCRIPTION:
Natural entrega
END DESCRIPTION:
XS GIS Cut Line= 6
    1074294.1034     1572816.087    1074341.2283    1573203.2294
    1074321.0168    1573239.0549    1074204.6368    1573182.7241
    1074134.8528    1573197.2763    1074002.0028     1573628.624
#Sta/Elev= 24
       0   64.08   67.22    64.5  263.62    64.5  303.38      65  367.67      65
  369.72   64.94  373.31      65  440.71      65  455.92    64.5   459.7      64
  462.65    63.5  465.46   63.31  468.67   61.55  470.75   61.55  472.97   63.35
  477.84      64  483.82    64.5  616.26    64.5  628.94   64.75   670.4      65
  748.23      65  937.24      64 1033.94   63.98 1090.67    63.6
#Mann= 3 , 0 , 0
       0    .035       0  440.71    .018       0   670.4    .035       0
Levee=-1,429.5,65,-1,673.39,65,,
Bank Sta=440.71,670.4
XS Rating Curve= 0 ,0
Pilot Channel=61.548,60,0.018
Exp/Cntr=0.3,0.1

Type RM Length L Ch R = 1 ,800.0468,171.38,200.05,152.94
BEGIN DESCRIPTION:
Natural entrega
END DESCRIPTION:
XS GIS Cut Line= 6
    1074201.2345    1572793.3328    1074191.8097    1572971.5487
    1074200.7204    1573157.4253    1074111.5405    1573169.8356
    1074055.1842    1573252.6504    1073963.9027    1573614.0719
#Sta/Elev= 30
       0    64.5  193.71    64.5  204.47      65   209.4   65.41  211.11   65.44
  221.63   64.95  248.33   64.68  268.99   64.69  281.96    64.5   288.6      64
  293.57    63.5  293.96   63.26  294.89      63  298.62    62.5  299.76    62.5
  305.81      62  308.79   61.29  309.52   61.29  311.51      62  319.51    63.5
  329.11    64.5  404.95    64.5  495.72   64.77  543.24    64.5  561.83    64.5
  573.22   64.63  619.07   64.76  767.17      64  871.01   63.86  927.54   63.57
#Mann= 3 , 0 , 0
       0    .035       0  281.96    .018       0  329.11    .035       0
Levee=-1,258.25,64.68,-1,495.5,64.77,,
Bank Sta=281.96,329.11
XS Rating Curve= 0 ,0
Pilot Channel=61.286,60,0.018
Exp/Cntr=0.3,0.1

Type RM Length L Ch R = 1 ,600     ,201.9,200,218.01
BEGIN DESCRIPTION:
Natural entrega
END DESCRIPTION:
XS GIS Cut Line= 5
    1074008.6174     1572759.466    1074030.2323    1572901.4454
    1074124.9951    1573025.8185    1074037.9862    1573171.6877
    1073937.4443    1573607.7219
#Sta/Elev= 20
       0      64   78.46      64  108.31    64.5  215.89    64.5  222.13      64
  224.65    63.5  232.46   61.27  233.18      61  239.72      61  243.46    61.5
  253.42    63.5   257.3      64  266.76    64.5  404.91    64.5  492.16   64.41
  528.45    64.5  653.76    64.5  734.64      64  859.78   63.78   917.3    63.5
#Mann= 3 , 0 , 0
       0    .035       0  215.89    .018       0  266.76    .035       0
Levee=-1,199.77,64.5,-1,274.69,64.5,,
Bank Sta=215.89,266.76
XS Rating Curve= 0 ,0
Pilot Channel=61.024,60,0.018
Exp/Cntr=0.3,0.1

Type RM Length L Ch R = 1 ,399.9999,192.3,200,207.7
BEGIN DESCRIPTION:
Natural entrega
END DESCRIPTION:
XS GIS Cut Line= 4
    1073767.3169     1572746.766    1073833.6822     1572915.828
    1074012.6483    1573073.2531    1073911.2505    1573601.9011
#Sta/Elev= 23
       0    63.5   67.28    63.5  184.11      64   297.1      64  300.15    63.5
  309.74    61.5  311.56   60.76  314.33   60.76  315.67    61.5  318.91      62
  324.11    63.5  326.74      64   387.3      64   403.9   64.22  419.97   64.27
  526.46   64.23  618.64   64.48  681.57    64.5  746.05      64  811.16   63.81
   898.1   63.69  934.08    63.5  958.26    63.5
#Mann= 3 , 0 , 0
       0    .035       0   297.1    .018       0  326.74    .035       0
Levee=-1,295.66,64,-1,328.24,64,,
Bank Sta=297.1,326.74
XS Rating Curve= 0 ,0
Pilot Channel=60.762,60,0.018
Exp/Cntr=0.3,0.1

Type RM Length L Ch R = 1 ,200     ,205.41,200,196.46
BEGIN DESCRIPTION:
Natural entrega
END DESCRIPTION:
XS GIS Cut Line= 4
    1073640.3167    1572763.6994    1073700.5868    1573007.8409
    1073879.6812    1573275.1143    1073830.8171     1573589.201
#Sta/Elev= 19
       0   63.07   48.22    63.5  205.12    63.5     314      64  367.72      64
  379.18    63.5  394.34   61.21  398.95   60.66  401.86    60.5  402.68   60.54
  403.56   60.72  413.06      63  416.37    63.5  422.34      64  428.89      64
  523.01   63.94  620.22      64   735.4    63.5  891.07    63.5
#Mann= 3 , 0 , 0
       0    .035       0  367.72    .018       0  428.89    .035       0
Levee=-1,366.33,64,-1,423.29,64,,
Bank Sta=367.72,428.89
XS Rating Curve= 0 ,0
Pilot Channel=60.5,60,0.018
Exp/Cntr=0.3,0.1
LCMann Table=0

Chan Stop Cuts=-1
Use User Specified Reach Order=0
Composite Channel Slope=5

--- HECRAS_v2.g02 (geometry) ---

Geom Title=HECRAS_v2a
Program Version=5.03

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
River Reach=ARROYOELZORRO   ,ARRIBALAT1

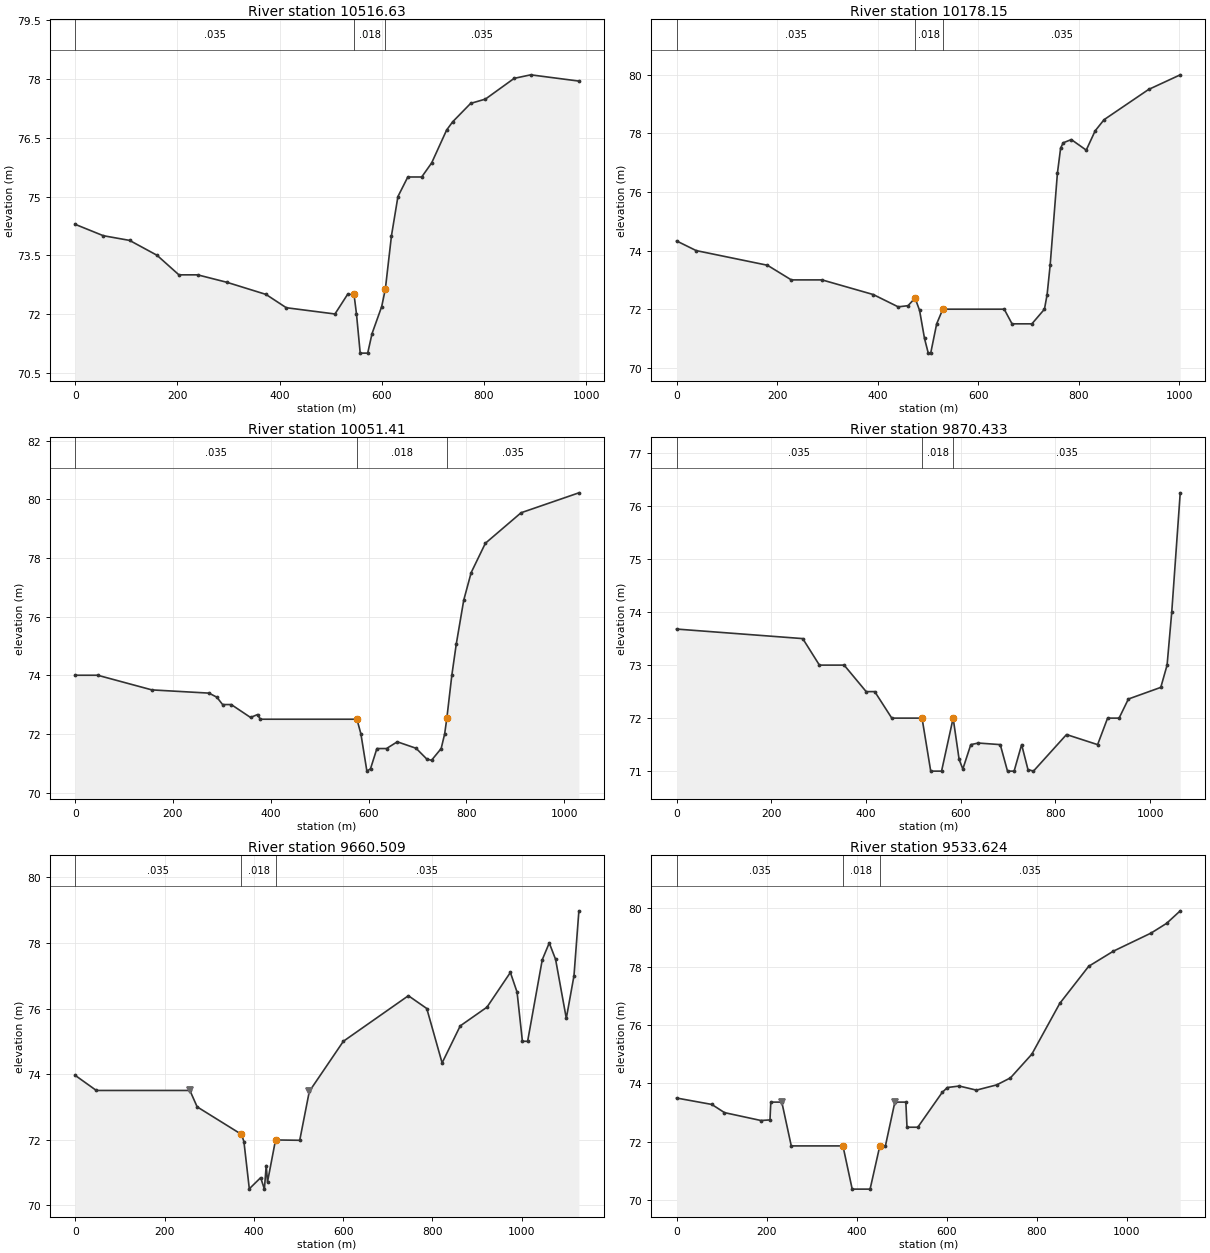
Type RM Length L Ch R = 1 ,10516.63,326.71,338.48,272.19
XS GIS Cut Line= 4
    1080327.0311    1572922.9204    1080508.3292    1573234.2431
    1080782.3396     1573544.788    1080904.0514    1573717.6348
#Sta/Elev= 30
       0   74.29   54.96      74  106.41   73.88  160.09    73.5  202.95      73
  239.59      73  296.77   72.81  373.39    72.5  413.09   72.16  508.37      72
  533.01    72.5  545.68    72.5   550.5      72  557.78      71  572.44      71
  580.98    71.5  599.85   72.19  607.03   72.64  618.98      74  631.62      75
  650.95    75.5  678.17    75.5  697.65   75.86  726.96    76.7  738.77   76.91
  773.94   77.38  802.87   77.49  859.15   78.02   891.6   78.11  985.81   77.95
#Mann= 3 , 0 , 0
       0    .035       0  545.68    .018       0  607.03    .035       0
Bank Sta=545.68,607.03
XS Rating Curve= 0 ,0
Exp/Cntr=0.3,0.1

Type RM Length L Ch R = 1 ,10178.15,130.71,126.74,122.71
XS GIS Cut Line= 4
    1080274.1143    1572941.9705    1080377.2263    1573318.1105
    1080566.5631    1573560.6676    1080749.9587    1573803.7037
#Sta/Elev= 30
       0   74.33   39.05      74  180.78    73.5  228.31      73  289.46      73
  391.35    72.5  440.96   72.08  460.63   72.12  474.55   72.38  483.53   71.96
  493.37      71  500.83    70.5  505.67    70.5  517.56    71.5  529.76      72
  651.94      72  667.53    71.5  707.05    71.5  732.02      72  737.33    72.5
  743.35    73.5  757.79   76.64  764.21    77.5  769.34   77.68  785.48   77.79
  815.14   77.43  832.97   78.09  850.74   78.47  939.19    79.5 1002.19      80
#Mann= 3 , 0 , 0
       0    .035       0  474.55    .018       0  529.76    .035       0
Bank Sta=474.55,529.76
XS Rating Curve= 0 ,0
Exp/Cntr=0.3,0.1

Type RM Length L Ch R = 1 ,10051.41,150.51,180.98,211.46
XS GIS Cut Line= 4
    1080240.2476    1572950.4372    1080352.9475    1573475.0008
     1080541.224    1573663.8071    1080671.8044    1573849.7252
#Sta/Elev= 30
       0      74   45.82      74  156.83    73.5  273.69   73.39   289.8   73.25
  301.48      73  319.19      73  358.67   72.56  373.11   72.66  378.61    72.5
  576.26    72.5  584.43      72  596.67   70.73  604.06   70.81  617.13    71.5
  636.79    71.5  658.87   71.73  697.24   71.51  719.35   71.14  728.91    71.1
  748.62    71.5  755.78      72  760.27   72.54  770.45      74  779.39   75.05
   794.8   76.56     810    77.5  839.05    78.5  912.04   79.54 1030.37   80.22
#Mann= 3 , 0 , 0
       0    .035       0  576.26    .018       0  760.27    .035       0
Bank Sta=576.26,760.27
XS Rating Curve= 0 ,0
Exp/Cntr=0.3,0.1

Type RM Length L Ch R = 1 ,9870.433,205.56,209.92,222.26
XS GIS Cut Line= 4
    1080202.1475    1572954.6705    1080254.1813     1573378.091
    1080194.4311    1573650.0588     1080377.746    1573958.0837
#Sta/Elev= 30
       0   73.68  266.43    73.5  301.61      73  353.82      73  400.36    72.5
  418.46    72.5  454.44      72  518.34      72  536.65      71  559.54      71
  584.02      72  596.64   71.22  604.48   71.04  621.28    71.5  637.17   71.53
   683.5    71.5  698.79      71  712.74      71  728.62    71.5  741.99   71.03
  753.58      71  823.39   71.69  889.07    71.5  910.13      72   934.4      72
  953.99   72.36 1022.46   72.58 1035.75      73 1045.59      74 1063.51   76.25
#Mann= 3 , 0 , 0
       0    .035       0  518.34    .018       0  584.02    .035       0
Bank Sta=518.34,584.02
XS Rating Curve= 0 ,0
Exp/Cntr=0.3,0.1

Type RM Length L Ch R = 1 ,9660.509,133.24,126.88,116.59
XS GIS Cut Line= 5
    1080161.9306    1572958.9446    1080152.5873    1573251.4818
    1080095.9811    1573338.1023    1079991.8435    1573479.1967
    1080234.5059    1573980.1218
#Sta/Elev= 30
       0   73.96   47.29    73.5  256.84    73.5  273.09      73  372.39   72.16
  377.86   71.94  389.93    70.5  415.39   70.84   423.7   70.49  427.79   71.21
  430.69   70.71  448.67   71.99  502.86   71.98  524.29   73.47  600.56      75
  746.21   76.39  787.41      76  821.77   74.34  862.37   75.47  922.19   76.04
  974.68    77.1  989.65    76.5 1001.61      75 1013.29      75 1046.13   77.49
 1061.74      78 1075.93    77.5 1099.93    75.7 1117.14      77 1128.13   78.98
#Mann= 3 , 0 , 0
       0    .035       0  372.39    .018       0  448.67    .035       0
Levee=-1,256.84,73.5,-1,524.29,73.47035,,	451
Bank Sta=372.39,448.67
XS Rating Curve= 0 ,0
Exp/Cntr=0.3,0.1

Type RM Length L Ch R = 1 ,9533.624,62.94,98.04,133.14
XS GIS Cut Line= 5
    1080109.3166     1572950.726    1080050.9978    1573155.8972
     1079943.577     1573386.726    1079923.5675    1573427.4895
    1079827.7994    1574025.7831
#Sta/Elev= 30
       0    73.5   78.34   73.28   106.5      73  187.46   72.73  207.56   72.75
  209.43   73.36  233.88   73.36  254.88   71.86  369.71   71.86  390.29   70.38
  430.04   70.38  451.65   71.86  464.08   71.86  485.08   73.36  509.48   73.36
  512.06    72.5  536.06    72.5  590.18   73.69  601.72   73.86  628.31   73.91
   666.3   73.77  711.47   73.95  741.98   74.19  789.41      75  851.53   76.74
  915.75   78.01  970.82   78.53 1054.62   79.15 1088.83   79.48 1119.22   79.91
#Mann= 3 , 0 , 0
       0    .035       0  369.71    .018       0  451.65    .035       0
Levee=-1,233.88,73.36314,-1,485.08,73.36273,	452,	451
Bank Sta=369.71,451.65
XS Rating Curve= 0 ,0
Exp/Cntr=0.3,0.1

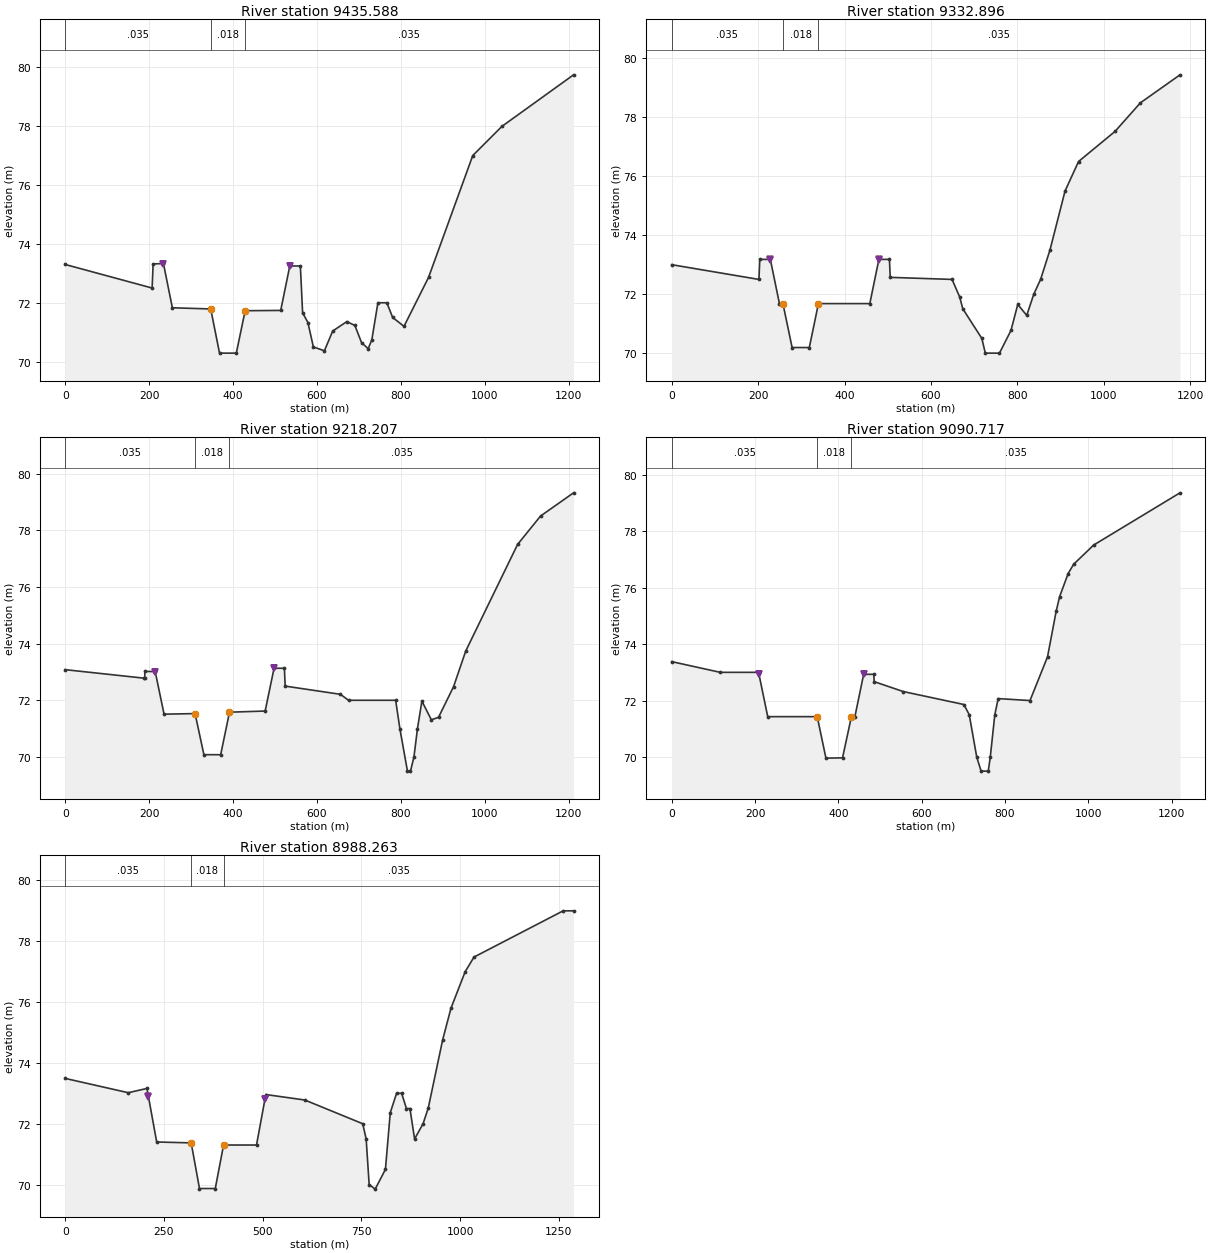
Type RM Length L Ch R = 1 ,9435.588,137.8,102.69,67.58
XS GIS Cut Line= 4
    1080083.4932    1572937.8142    1079991.2064    1573234.1482
     1079861.851     1573271.218    1079719.4258    1574024.0897
#Sta/Elev= 30
       0    73.3  207.07    72.5  209.48   73.32   234.1   73.33  255.29   71.83
   346.7   71.79   367.7   70.29   407.7   70.29   428.7   71.73  513.46   71.74
  535.12   73.25   560.3   73.25  565.65   71.66  578.22   71.33   591.3    70.5
   617.6   70.37  637.36   71.04  670.92   71.36  690.23   71.23  705.96   70.65
  721.87   70.44  730.54   70.74  745.07      72   766.4      72  780.24    71.5
  807.22    71.2  865.68   72.86  971.08      77 1040.58   77.99 1211.16   79.74
#Mann= 3 , 0 , 0
       0    .035       0   346.7    .018       0   428.7    .035       0
Levee=-1,234.1,73.32671,-1,535.13,73.24612,	452,	451
Bank Sta=346.7,428.7
XS Rating Curve= 0 ,0
Exp/Cntr=0.3,0.1

Type RM Length L Ch R = 1 ,9332.896,141.46,114.69,87.92
XS GIS Cut Line= 3
    1079992.4764    1572899.5025    1079778.3077     1573359.714
    1079621.0007    1574009.6964
#Sta/Elev= 30
       0      73  201.91    72.5  203.94   73.18  228.34   73.18  249.34   71.68
  257.43   71.68  278.72   70.19  318.56   70.19  339.62   71.68  458.54   71.68
  479.54   73.18  503.94   73.18  505.77   72.57  648.86    72.5  666.35   71.91
  673.85    71.5  717.72    70.5  725.81      70  758.58      70   785.2   70.77
  800.92   71.65  821.68   71.28  838.01      72  853.74    72.5  875.49    73.5
  910.34    75.5  941.61    76.5 1025.97   77.52 1084.68   78.49 1176.35   79.44
#Mann= 3 , 0 , 0
       0    .035       0  257.43    .018       0  339.62    .035       0
Levee=-1,228.34,73.17561,-1,479.54,73.17561,	452,	451
Bank Sta=257.43,339.62
XS Rating Curve= 0 ,0
Exp/Cntr=0.3,0.1

Type RM Length L Ch R = 1 ,9218.207,100.72,127.49,154.26
XS GIS Cut Line= 5
    1079875.0012    1572860.7674    1079739.5342    1573104.6079
    1079763.8079    1573214.4359    1079771.7076    1573257.0082
    1079542.2605    1573998.6897
#Sta/Elev= 30
       0   73.08  188.03   72.78  189.26   72.78  189.98   73.02  214.44   73.01
   235.5   71.51  309.42   71.53  330.42   70.08  370.42   70.08  391.42   71.58
  476.37   71.62  497.57   73.13  522.19   73.13  524.11    72.5  655.81   72.21
  674.96      72  787.28      72  797.42   70.99  815.42    69.5   822.6    69.5
  830.88      70  839.26      71  849.81   71.97  872.36   71.31  889.48    71.4
  925.24   72.48  954.33   73.74 1077.82    77.5 1132.44    78.5 1211.08   79.32
#Mann= 3 , 0 , 0
       0    .035       0  309.42    .018       0  391.42    .035       0
Levee=-1,214.44,73.01493,-1,497.56,73.12814,	452,	451
Bank Sta=309.42,391.42
XS Rating Curve= 0 ,0
Exp/Cntr=0.3,0.1

Type RM Length L Ch R = 1 ,9090.717,68.21,102.45,136.69
XS GIS Cut Line= 3
    1079795.4143     1572828.594    1079590.7473    1573268.3881
    1079386.4735    1573974.1363
#Sta/Elev= 30
       0   73.38  116.52      73  206.87      73  208.66   72.99  230.48   71.43
  349.22   71.43  370.18   69.96  410.01   69.97  431.31   71.43  439.68   71.43
  460.68   72.93  485.08   72.93   485.9   72.67  555.56   72.32  701.25   71.86
  714.03    71.5  732.03      70  742.52    69.5  759.73    69.5  764.57      70
  775.42    71.5  783.49   72.07  859.84      72  901.93   73.55  922.59   75.16
  930.92   75.68   951.4    76.5  964.59   76.83 1012.64   77.51  1219.8   79.36
#Mann= 3 , 0 , 0
       0    .035       0  349.22    .018       0  431.31    .035       0
Levee=-1,209.48,72.93304,-1,460.68,72.93301,	452,	451
Bank Sta=349.22,431.31
XS Rating Curve= 0 ,0
Exp/Cntr=0.3,0.1

Type RM Length L Ch R = 1 ,8988.263,137.11,103.08,68.73
XS GIS Cut Line= 4
    1079759.8543     1572810.814     1079645.554    1573077.6204
    1079521.3471    1573116.0751    1079286.2491    1573950.7471
#Sta/Elev= 30
       0   73.49  159.73   73.02  207.05   73.16  231.71    71.4  319.07   71.37
  340.07   69.87  380.07   69.87  401.07    71.3  484.52    71.3  508.09   72.96
  606.87   72.78   753.5      72  762.21    71.5  769.83      70  785.04   69.85
  811.06    70.5  823.24   72.36   839.2      73   852.1      73  864.25    72.5
   873.1    72.5  884.88    71.5  906.36      72  919.57   72.52     956   74.76
  977.07    75.8 1012.99      77  1035.4   77.48 1261.22      79 1287.43      79
#Mann= 3 , 0 , 0
       0    .035       0  319.07    .018       0  401.07    .035       0
Levee=-1,210.7,72.89437,-1,505.8,72.80102,	452,	451
Bank Sta=319.07,401.07
XS Rating Curve= 0 ,0
Exp/Cntr=0.3,0.1