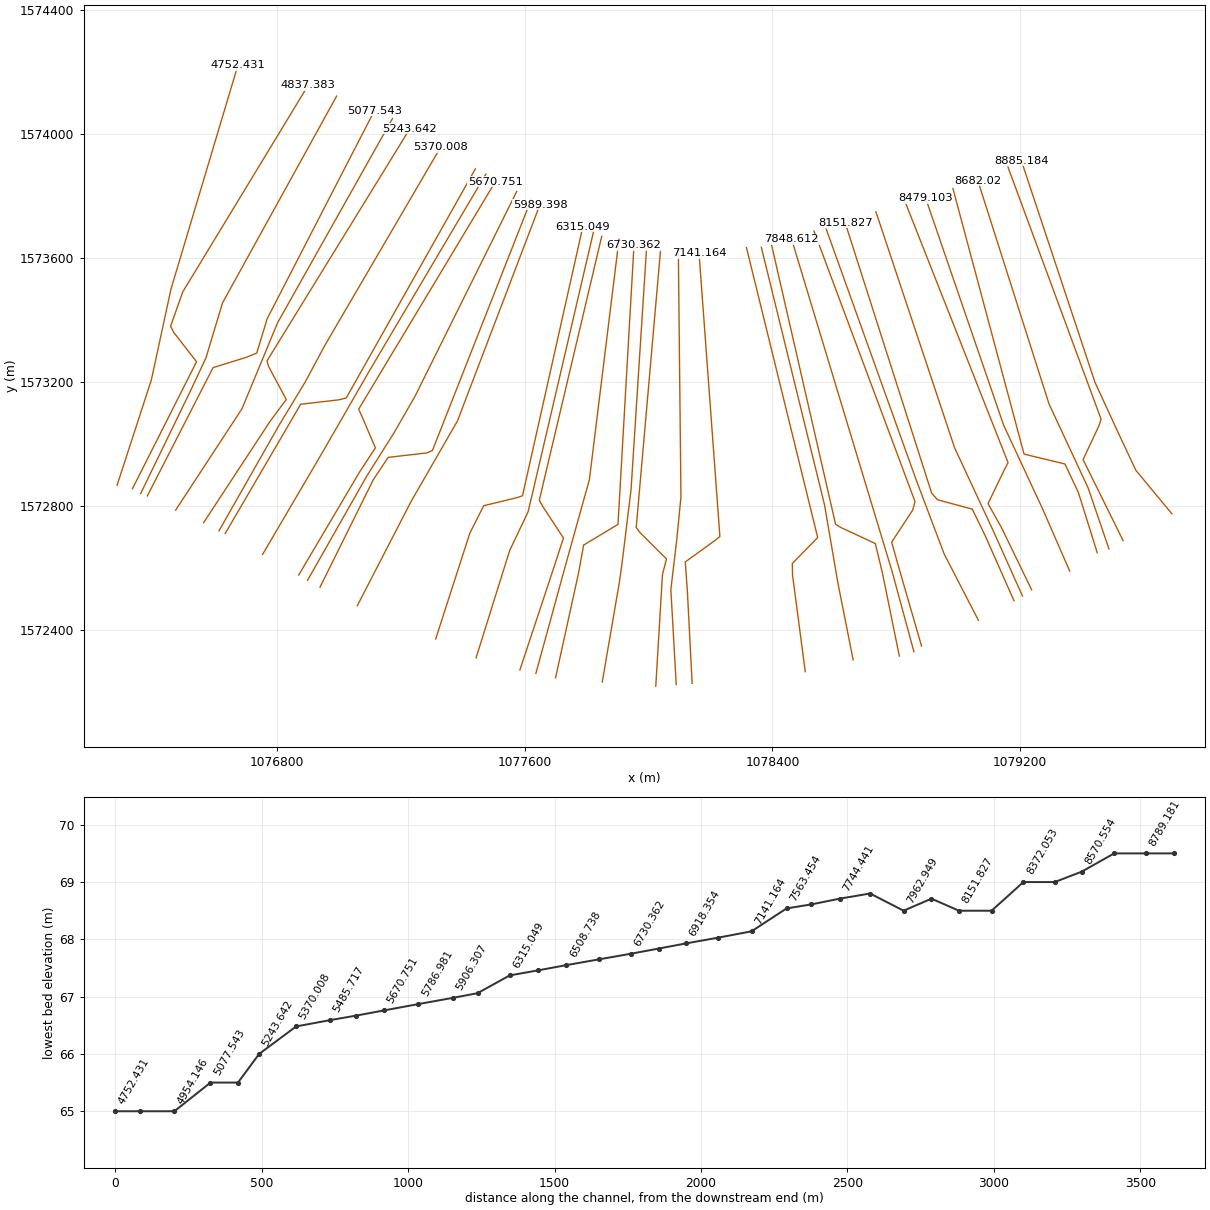
HEC-RAS study HECRAS_v2.prj: HECRAS_v2

--- HECRAS_v2.g02 (geometry) --- (continued)

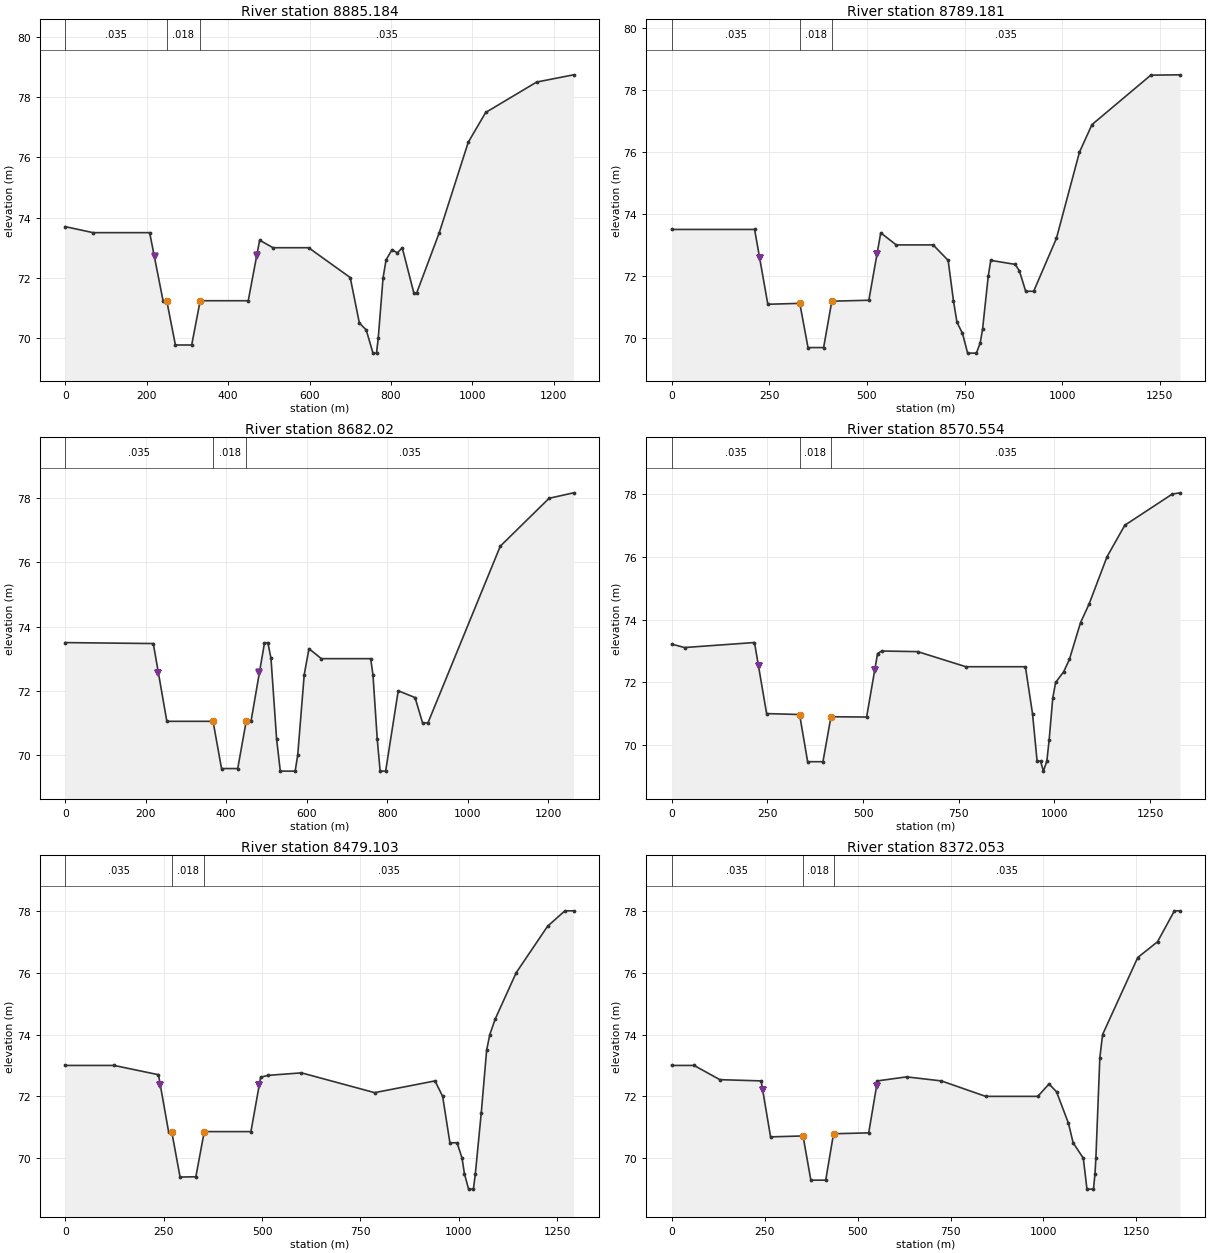
Type RM Length L Ch R = 1 ,8885.184,132.08,96,60.24
XS GIS Cut Line= 5
    1079689.4749    1572775.0158    1079573.3755    1572915.1394
    1079527.1627    1573013.1873     1079441.341    1573198.8588
    1079203.8048    1573913.9964
#Sta/Elev= 30
       0    73.7   68.38    73.5  207.42    73.5  240.31   71.24  249.34   71.24
  270.65   69.77  310.66   69.77  331.47   71.24  449.51   71.24  477.54   73.25
  510.44      73  597.78      73  699.99   72.01  722.46    70.5  739.33   70.27
  755.91    69.5  764.56    69.5  768.83      70  780.68      72  788.11    72.6
  802.42   72.93  815.94   72.83  827.78      73  856.22    71.5  863.31    71.5
  918.75    73.5  989.86    76.5 1032.67   77.49 1157.89    78.5 1248.47   78.74
#Mann= 3 , 0 , 0
       0    .035       0  249.34    .018       0  331.47    .035       0
Levee=-1,219.31,72.74111,-1,470.51,72.74126,	452,	451
Bank Sta=249.34,331.47
XS Rating Curve= 0 ,0
Exp/Cntr=0.3,0.1

Type RM Length L Ch R = 1 ,8789.181,71.26,107.16,143.04
XS GIS Cut Line= 5
    1079531.8761    1572688.6196    1079402.7592    1572950.0285
    1079453.2203    1573057.3448    1079460.9676    1573080.2037
    1079160.4004    1573894.0637
#Sta/Elev= 30
       0    73.5   212.4    73.5  246.26   71.08  328.15   71.11  349.15   69.68
  389.15   69.68  410.15   71.18  504.98   71.21  535.47   73.39  575.11      73
  669.62      73  708.06    72.5  721.73   71.19  730.62    70.5  744.79   70.14
  757.94    69.5  780.38    69.5  790.23   69.83  796.36   70.29  810.78   71.99
  817.23    72.5  879.82   72.37   890.5   72.16  906.69    71.5  927.07    71.5
  985.34   73.21 1044.39      76 1076.42   76.89 1227.07   78.49 1301.87    78.5
#Mann= 3 , 0 , 0
       0    .035       0  328.15    .018       0  410.15    .035       0
Levee=-1,225.26,72.58036,-1,526.05,72.71256,	452,	451
Bank Sta=328.15,410.15
XS Rating Curve= 0 ,0
Exp/Cntr=0.3,0.1

Type RM Length L Ch R = 1 ,8682.02 ,74.63,111.47,148.33
XS GIS Cut Line= 4
    1079486.3677    1572661.6321    1079419.3723    1572857.7406
    1079292.7963    1573129.7306    1079063.1393    1573850.2486
#Sta/Elev= 30
       0    73.5  218.95   73.47  252.64   71.05  367.49   71.05  388.54   69.58
  428.82   69.58  449.82   71.05  461.84   71.05  495.23   73.48  503.71    73.5
  511.46   73.01  525.43    70.5  534.64    69.5  571.54    69.5  577.94      70
  594.06    72.5   605.9   73.31  636.65      73  759.24      73  764.93    72.5
  775.55    70.5  782.78    69.5  796.46    69.5  827.74      72  869.52   71.79
  888.28      71  901.54      71 1081.42    76.5 1202.71   77.99 1263.47   78.16
#Mann= 3 , 0 , 0
       0    .035       0  367.49    .018       0  449.82    .035       0
Levee=-1,231.64,72.55075,-1,482.84,72.55075,	452,	451
Bank Sta=367.49,449.82
XS Rating Curve= 0 ,0
Exp/Cntr=0.3,0.1

Type RM Length L Ch R = 1 ,8570.554,128.33,91.45,54.52
XS GIS Cut Line= 6
    1079448.3734    1572649.6729    1079387.8709    1572843.0808
    1079344.2332    1572935.8468    1079236.2393    1572961.8225
     1079212.153    1572968.0202    1078982.7058    1573824.8486
#Sta/Elev= 30
       0   73.22   33.56   73.11  216.39   73.27  248.05   71.01  334.24   70.98
  355.24   69.48  395.24   69.48  416.24   70.91  509.33    70.9  537.96   72.92
  548.72      73  642.69   72.98  768.63    72.5  924.21    72.5  942.88      71
  954.78    69.5  963.72    69.5   971.2   69.18  980.22    69.5  986.24   70.17
  995.65    71.5 1003.15      72 1024.17   72.34 1039.11   72.73 1068.18    73.9
 1090.81    74.5 1137.54      76 1183.97      77 1307.88   77.99 1328.13   78.03
#Mann= 3 , 0 , 0
       0    .035       0  334.24    .018       0  416.24    .035       0
Levee=-1,227.05,72.51025,-1,530.65,72.40443,	452,	451
Bank Sta=334.24,416.24
XS Rating Curve= 0 ,0
Exp/Cntr=0.3,0.1

Type RM Length L Ch R = 1 ,8479.103,143.28,107.05,70.86
XS GIS Cut Line= 4
    1079359.4733    1572590.4061    1079272.7216    1572789.4938
    1079146.1456    1573061.4837    1078894.6523    1573793.5218
#Sta/Elev= 30
       0      73  124.03      73  236.91    72.7  262.57   70.86  270.55   70.86
  291.77   69.39  331.85    69.4  353.22   70.86  471.77   70.86  496.41   72.62
  515.77   72.68  600.11   72.76  786.04   72.12  939.38    72.5  958.72      72
  977.18    70.5  995.44    70.5 1008.04      70 1014.04    69.5  1024.6      69
 1036.88      69 1041.74   69.49 1056.77   71.46 1070.55    73.5 1078.59      74
 1092.19    74.5  1145.6      76 1225.17    77.5 1269.16      78  1291.2      78
#Mann= 3 , 0 , 0
       0    .035       0  270.55    .018       0  353.22    .035       0
Levee=-1,241.57,72.36261,-1,492.77,72.36261,	452,	451
Bank Sta=270.55,353.22
XS Rating Curve= 0 ,0
Exp/Cntr=0.3,0.1

Type RM Length L Ch R = 1 ,8372.053,72.42,108.66,144.91
XS GIS Cut Line= 6
    1079236.8122    1572529.6153    1079140.6199    1572728.0176
    1079096.0536    1572807.9575    1079149.5197     1572919.071
     1079160.612    1572940.2495    1078827.2364    1573784.8012
#Sta/Elev= 30
       0      73   60.21      73  129.66   72.54  240.63    72.5  266.01   70.69
  353.32   70.72  374.32   69.29  414.32   69.29  435.32   70.79  529.97   70.82
  553.46    72.5   631.7   72.63  725.27    72.5  844.52      72  984.74      72
 1014.89    72.4 1035.04   72.15 1067.22   71.13 1079.68    70.5 1107.13      70
 1116.99      69 1134.46      69  1138.6    69.5 1140.94      70  1151.6   73.25
 1159.01      74 1253.53   76.49 1306.77      77 1352.15      78  1367.2      78
#Mann= 3 , 0 , 0
       0    .035       0  353.32    .018       0  435.32    .035       0
Levee=-1,244.96,72.19109,-1,551.01,72.32472,	452,	451
Bank Sta=353.32,435.32
XS Rating Curve= 0 ,0
Exp/Cntr=0.3,0.1

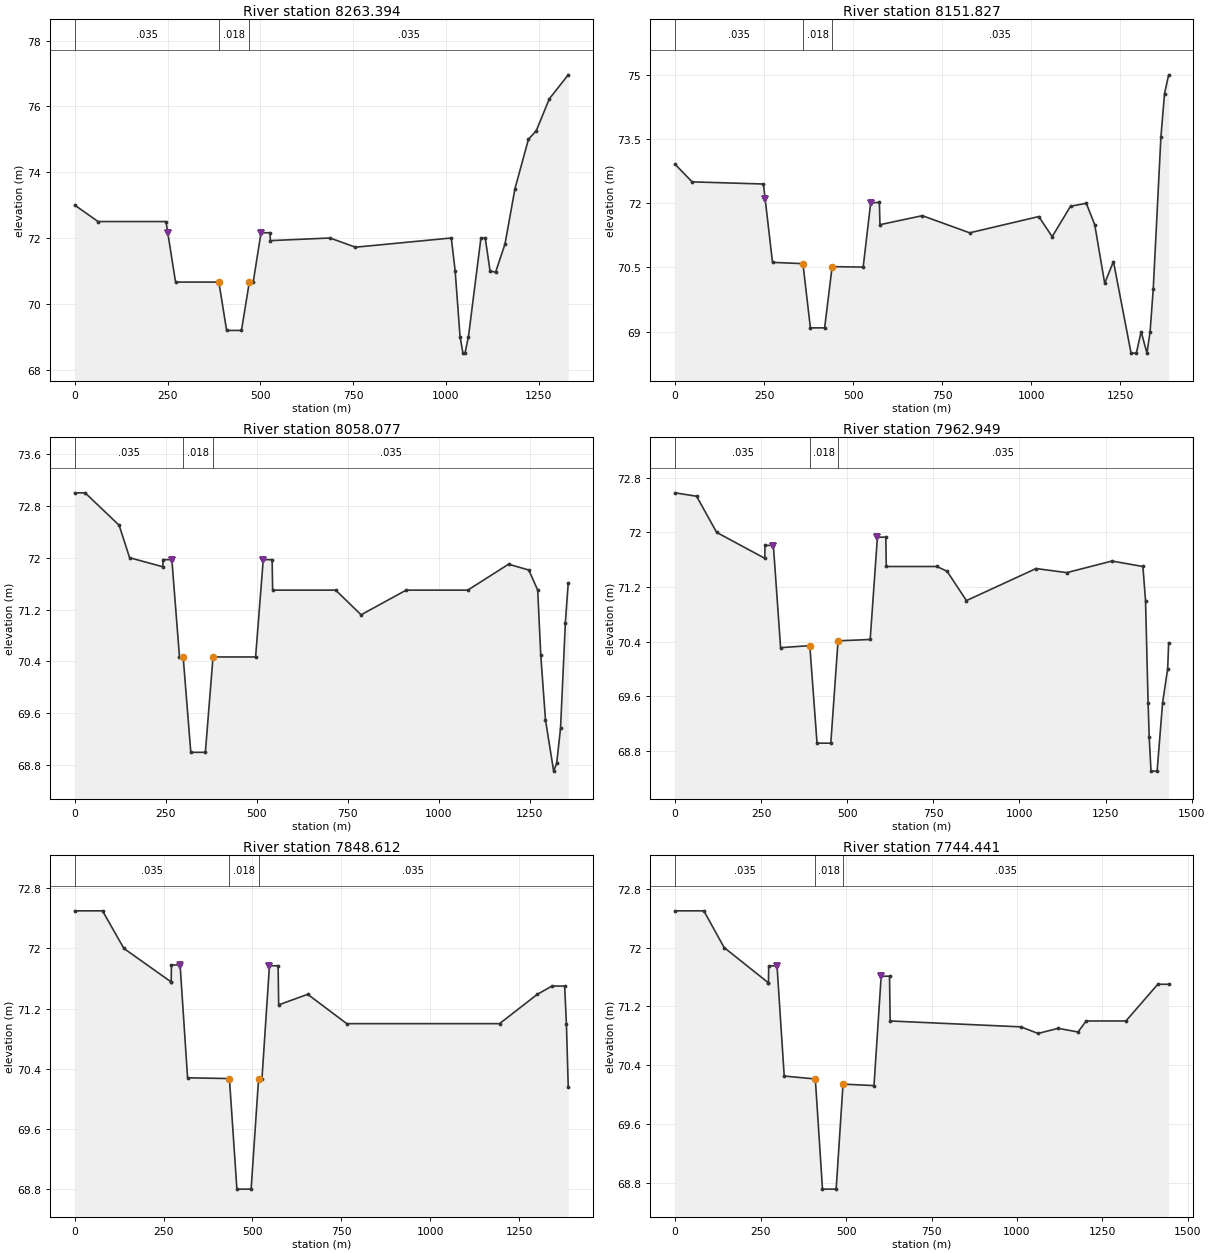
Type RM Length L Ch R = 1 ,8263.394,75.89,111.57,147.24
XS GIS Cut Line= 4
    1079207.1788    1572509.5069    1079114.7195    1572715.9643
    1078988.1435    1572987.9543    1078734.1028    1573749.8761
#Sta/Elev= 30
       0      73   62.84    72.5  245.85    72.5  271.62   70.66  388.31   70.66
  409.19   69.19  449.23   69.19  470.35   70.66  480.82   70.66  501.82   72.16
  526.22   72.16  526.96   71.92  687.74      72  756.24   71.72 1014.35      72
 1024.78      71 1037.96      69 1045.76    68.5 1051.26    68.5 1060.57      69
 1094.21      72 1105.86      72 1118.71      71  1133.7   70.96 1159.07   71.82
  1185.9    73.5  1222.2      75 1243.25   75.26  1278.4   76.23 1329.37   76.96
#Mann= 3 , 0 , 0
       0    .035       0  388.31    .018       0  470.35    .035       0
Levee=-1,250.61,72.15994,-1,501.81,72.15994,	452,	451
Bank Sta=388.31,470.35
XS Rating Curve= 0 ,0
Exp/Cntr=0.3,0.1

Type RM Length L Ch R = 1 ,8151.827,132.49,93.75,55.01
XS GIS Cut Line= 6
    1079179.6621    1572494.6902    1079087.3428     1572703.224
    1079045.2535    1572789.9658    1078932.8887    1572820.4592
    1078914.0199    1572841.8243    1078634.6193     1573714.951
#Sta/Elev= 30
       0   72.91   47.57    72.5  247.93   72.45  273.46   70.62   358.9   70.59
   379.9   69.09   419.9   69.09   440.9   70.52  528.14   70.51   549.2   72.01
  573.68   72.02  575.23    71.5  694.23   71.71  827.29   71.31  1021.3   71.69
 1058.96   71.22 1110.43   71.93 1154.79      72 1178.52    71.5 1206.48   70.13
 1231.08   70.64 1280.53    68.5 1295.36    68.5 1308.85      69 1325.22    68.5
 1333.96      69 1342.84      70 1364.31   73.54 1374.45   74.56 1386.14      75
#Mann= 3 , 0 , 0
       0    .035       0   358.9    .018       0   440.9    .035       0
Levee=-1,252.93,72.09,-1,549.29,72.01389,	452,	451
Bank Sta=358.9,440.9
XS Rating Curve= 0 ,0
Exp/Cntr=0.3,0.1

Type RM Length L Ch R = 1 ,8058.077,133.73,95.13,56.53
XS GIS Cut Line= 4
    1079064.8327    1572431.4018    1078954.4105    1572645.2909
    1078864.4802    1572883.4531     1078573.765     1573693.996
#Sta/Elev= 30
       0      73   28.62      73  122.09    72.5  150.84      72  242.23   71.86
  242.56   71.97  266.96   71.97  287.96   70.47  298.06   70.47  319.05      69
  359.06      69  380.13   70.47  497.16   70.47  518.16   71.97  542.56   71.97
  543.98    71.5  717.22    71.5  787.06   71.12  910.99    71.5 1080.33    71.5
 1192.41    71.9 1247.99   71.81 1272.48    71.5 1280.85    70.5 1293.84    69.5
 1316.32   68.71 1324.62   68.83 1335.22   69.37  1348.5      71 1356.39   71.61
#Mann= 3 , 0 , 0
       0    .035       0  298.06    .018       0  380.13    .035       0
Levee=-1,267.02,71.96507,-1,518.24,71.9697,	452,	451
Bank Sta=298.06,380.13
XS Rating Curve= 0 ,0
Exp/Cntr=0.3,0.1

Type RM Length L Ch R = 1 ,7962.949,78.48,114.34,150.19
XS GIS Cut Line= 6
    1078881.4231    1572348.1108    1078808.8085    1572598.7291
    1078784.9029    1572683.3915    1078852.9902    1572787.2213
    1078860.2564    1572814.6251    1078534.2891    1573687.5401
#Sta/Elev= 30
       0   72.58   62.27   72.53  120.53      72   260.3   71.62  260.85   71.81
  285.25   71.81  306.25   70.31  391.06   70.34  412.06   68.91  452.06   68.91
  473.06   70.41  566.41   70.43  587.41   71.93  611.82   71.93  613.12    71.5
  760.06    71.5  789.68   71.43  846.01      71 1048.08   71.47 1137.27   71.41
  1268.4   71.58 1358.38    71.5 1366.04      71 1373.51    69.5 1376.66      69
 1381.93    68.5 1399.68    68.5 1415.51    69.5 1430.31      70  1433.2   70.38
#Mann= 3 , 0 , 0
       0    .035       0  391.06    .018       0  473.06    .035       0
Levee=-1,285.33,71.8001,-1,587.45,71.93429,	452,	451
Bank Sta=391.06,473.06
XS Rating Curve= 0 ,0
Exp/Cntr=0.3,0.1

Type RM Length L Ch R = 1 ,7848.612,69.71,104.17,138.64
XS GIS Cut Line= 4
    1078856.8697    1572329.4841    1078785.7915    1572590.9508
    1078698.8347    1572878.1138    1078462.3223    1573660.4468
#Sta/Elev= 24
       0    72.5   78.19    72.5  138.34      72   269.6   71.56  271.41   71.56
  272.06   71.78  296.47   71.78  317.48   70.28  435.19   70.27  456.24    68.8
  496.27    68.8  517.26   70.27  526.77   70.27  547.78   71.77  572.19   71.77
  573.73   71.25  655.46   71.39   765.3      71 1195.07      71 1301.31   71.39
 1342.69    71.5  1378.2    71.5 1383.16      71  1388.3   70.16
#Mann= 3 , 0 , 0
       0    .035       0  435.19    .018       0  517.26    .035       0
Levee=-1,296.55,71.77283,-1,547.83,71.7709,	452,	451
Bank Sta=435.19,517.26
XS Rating Curve= 0 ,0
Exp/Cntr=0.3,0.1

Type RM Length L Ch R = 1 ,7744.441,136.14,96.57,56.98
XS GIS Cut Line= 6
     1078809.668    1572315.7257    1078755.1603    1572583.9023
    1078732.1978    1572678.9464    1078622.8718     1572729.903
    1078603.9276    1572741.1766    1078396.2822    1573647.3234
#Sta/Elev= 25
       0    72.5   83.96    72.5  143.29      72  272.73   71.52  273.01   71.52
  273.66   71.75  298.06   71.75  319.07   70.25  410.06   70.21  431.06   68.71
  471.06   68.71  491.13   70.14  492.06   70.14  581.73   70.12   602.7   71.61
  627.12   71.61  628.96      71 1011.28   70.92 1061.62   70.83 1120.55    70.9
 1178.57   70.85 1202.39      71  1318.7      71 1411.92    71.5 1443.73    71.5
#Mann= 3 , 0 , 0
       0    .035       0  410.06    .018       0  492.06    .035       0
Levee=-1,298.06,71.74581,-1,602.75,71.61491,	452,	451
Bank Sta=410.06,492.06
XS Rating Curve= 0 ,0
Exp/Cntr=0.3,0.1

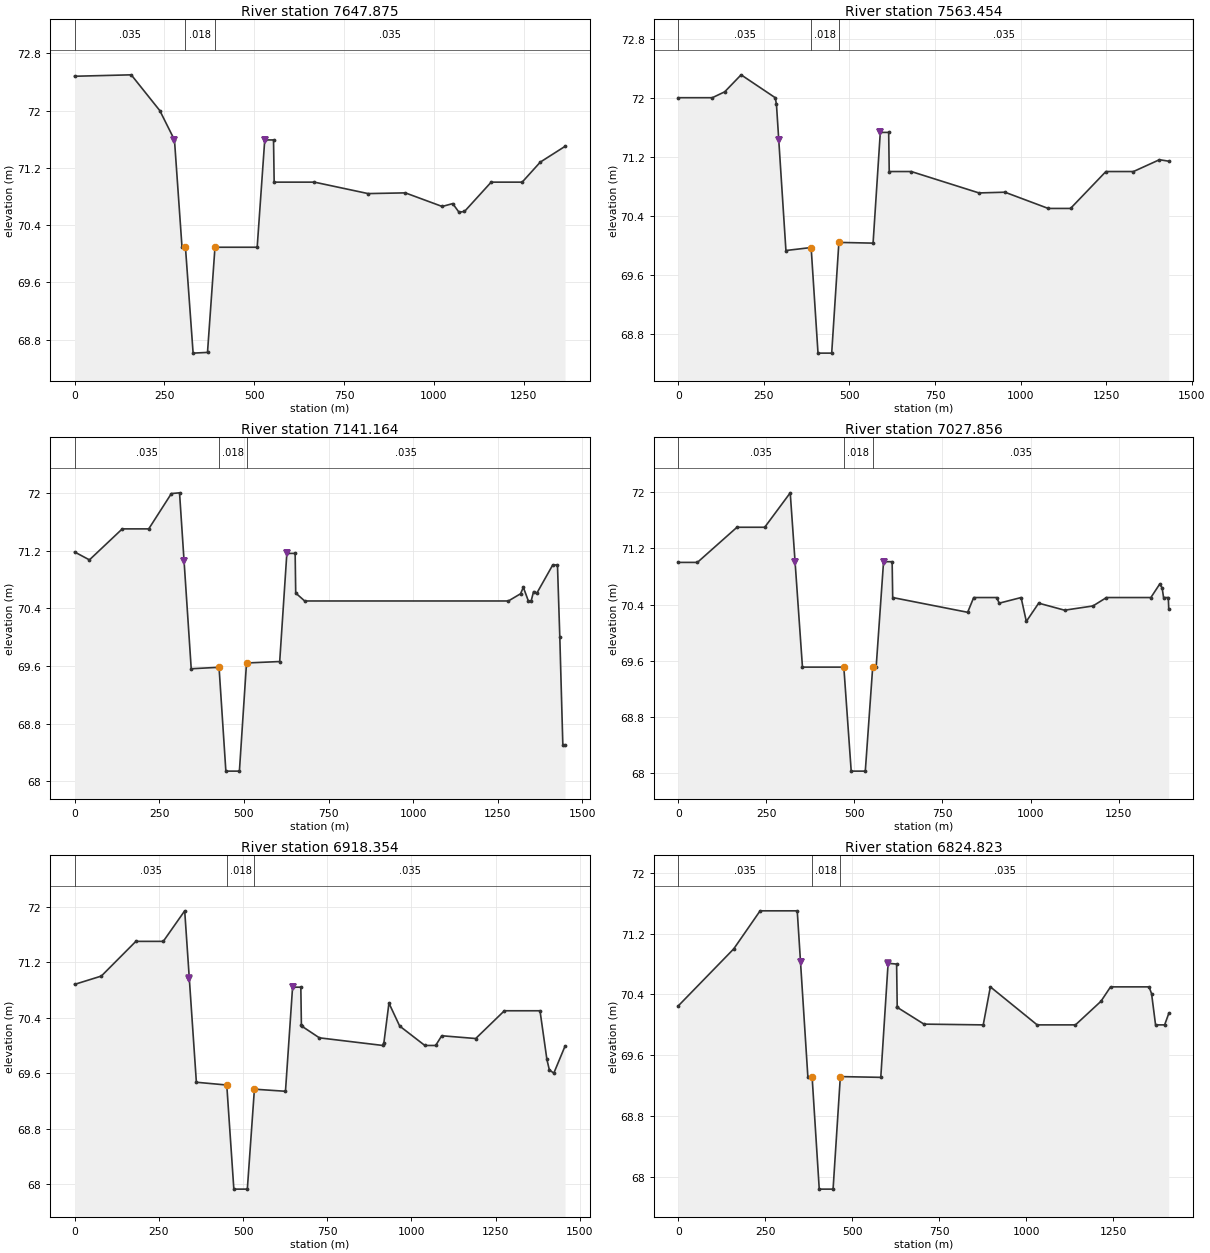
Type RM Length L Ch R = 1 ,7647.875,123.11,84.42,45.74
XS GIS Cut Line= 4
     1078660.612     1572303.449    1078611.3139    1572552.2751
    1078568.3847    1572803.1983    1078364.2781    1573635.2584
#Sta/Elev= 24
       0   72.48  157.71    72.5  237.24      72  278.04   71.59  299.04   70.09
  308.61   70.09  329.93   68.61  369.98   68.62  390.79   70.09  508.24   70.09
  529.28   71.59  553.73   71.59   555.5      71  667.43      71  816.89   70.84
  920.58   70.85 1023.06   70.66 1052.44    70.7 1069.75   70.58  1085.2   70.59
  1159.5      71 1245.72      71 1296.12   71.28 1364.96    71.5
#Mann= 3 , 0 , 0
       0    .035       0  308.61    .018       0  390.79    .035       0
Levee=-1,278.06,71.58556,-1,529.34,71.58855,	452,	451
Bank Sta=308.61,390.79
XS Rating Curve= 0 ,0
Exp/Cntr=0.3,0.1

Type RM Length L Ch R = 1 ,7563.454,84.95,119.85,154.72
XS GIS Cut Line= 5
     1078506.095     1572265.349    1078465.0065    1572577.1945
     1078464.185    1572614.5997    1078546.1793     1572698.458
    1078316.2297    1573634.4117
#Sta/Elev= 25
       0      72   99.46      72  135.64   72.08  183.54   72.31  283.25      72
  286.83   71.91  314.49   69.93  387.24   69.97  388.18   69.97  408.24   68.54
  448.24   68.54  469.24   70.04  569.16   70.03  590.24   71.53  614.73   71.53
  616.32      71  680.66      71  878.59   70.71  954.32   70.72 1081.03    70.5
 1146.05    70.5 1249.41      71 1329.96      71 1405.85   71.16 1433.03   71.14
#Mann= 3 , 0 , 0
       0    .035       0  387.24    .018       0  469.24    .035       0
Levee=-1,293.57,71.42873,-1,590.23,71.52978,	452,	451
Bank Sta=387.24,469.24
XS Rating Curve= 0 ,0
Exp/Cntr=0.3,0.1

Type RM Length L Ch R = 1 ,7141.164,78.58,113.31,148.04
XS GIS Cut Line= 6
    1078140.9693    1572227.8839    1078125.4875    1572526.2204
    1078118.7443    1572619.6797    1078212.2914    1572687.2832
    1078230.5045    1572701.5948    1078163.1944    1573616.6317
#Sta/Elev= 29
       0   71.18   43.91   71.07  140.93    71.5  219.06    71.5  285.94   71.99
  310.04      72  344.53   69.56  425.86   69.58  426.73   69.58  446.86   68.14
  486.86   68.14  507.86   69.64  605.87   69.66  626.97   71.16  651.49   71.16
  653.15   70.61  679.69    70.5 1281.23    70.5  1317.2    70.6 1325.42   70.69
 1340.26    70.5 1348.49    70.5 1355.67   70.63 1365.51   70.61 1412.31      71
 1426.23      71 1433.13      70 1442.11    68.5 1448.53    68.5
#Mann= 3 , 0 , 0
       0    .035       0  425.86    .018       0  507.86    .035       0
Levee=-1,323.4,71.05342,-1,626.99,71.16149,	452,	451
Bank Sta=425.86,507.86
XS Rating Curve= 0 ,0
Exp/Cntr=0.3,0.1

Type RM Length L Ch R = 1 ,7027.856,73.22,109.5,145.78
XS GIS Cut Line= 5
    1078089.5342    1572224.0739    1078072.2662    1572530.7353
    1078091.3989    1572692.3778    1078104.8158    1572829.0109
    1078096.5192    1573614.0916
#Sta/Elev= 30
       0      71   54.24      71  166.58    71.5  245.34    71.5  317.79   71.99
   352.5   69.51  469.92   69.51  490.89   68.03   530.9   68.03  551.91   69.51
  561.72   69.51  582.72   71.01  607.12   71.01  608.66    70.5  821.48   70.29
  838.62    70.5  903.76    70.5  911.13   70.42   973.2    70.5  988.04   70.16
 1023.09   70.42 1096.64   70.32 1177.09   70.38 1215.63    70.5 1341.61    70.5
 1366.45   70.69 1373.55   70.64 1377.63    70.5 1391.08    70.5 1392.33   70.34
#Mann= 3 , 0 , 0
       0    .035       0  469.92    .018       0  551.91    .035       0
Levee=-1,331.55,71.00288,-1,582.81,71.00985,	452,	451
Bank Sta=469.92,551.91
XS Rating Curve= 0 ,0
Exp/Cntr=0.3,0.1

Type RM Length L Ch R = 1 ,6918.354,130.83,93.53,56.23
XS GIS Cut Line= 6
    1078023.5364    1572218.3589    1078045.1515    1572579.2561
    1078058.2498    1572629.2047    1077972.8051    1572714.3585
    1077960.4596    1572730.8049    1078039.1998    1573628.6967
#Sta/Elev= 30
       0   70.88   79.45      71  181.95    71.5   263.3    71.5   326.9   71.94
  361.54   69.47  451.75   69.43  472.77   67.93   512.8   67.93  533.81   69.37
     626   69.34  647.09   70.84  671.59   70.84  673.27   70.29  673.92   70.28
  726.65   70.11  914.95      70  918.16   70.04  933.12   70.61  964.93   70.28
 1039.66      70 1071.76      70 1089.87   70.14 1190.63    70.1 1275.72    70.5
  1381.5    70.5  1401.9    69.8 1409.14   69.65 1422.37    69.6 1455.72   69.99
#Mann= 3 , 0 , 0
       0    .035       0  451.75    .018       0  533.81    .035       0
Levee=-1,340.59,70.9677,-1,647.12,70.84079,	452,	451
Bank Sta=451.75,533.81
XS Rating Curve= 0 ,0
Exp/Cntr=0.3,0.1

Type RM Length L Ch R = 1 ,6824.823,131.59,94.46,57.33
XS GIS Cut Line= 6
    1077850.8161    1572232.1172    1077906.1448    1572554.4187
    1077914.0826    1572610.7491     1077924.109    1572692.1077
    1077943.7248     1572852.662     1077993.903    1573633.3534
#Sta/Elev= 27
       0   70.25  159.44      71  235.22    71.5  341.95    71.5  372.44   69.32
   383.9   69.32  384.65   69.32  405.23   67.84  444.99   67.84  465.88   69.32
  582.12   69.31  603.17   70.81  627.63    70.8  629.35   70.24  629.69   70.23
  706.34   70.01  876.63      70  897.14    70.5 1031.73      70 1141.79      70
 1215.01   70.31 1242.65    70.5 1353.36    70.5  1360.6   70.41 1372.04      70
 1398.14      70 1409.93   70.15
#Mann= 3 , 0 , 0
       0    .035       0   383.9    .018       0  465.88    .035       0
Levee=-1,351.45,70.82193,-1,603.18,70.8055,	452,	451
Bank Sta=383.9,465.88
XS Rating Curve= 0 ,0
Exp/Cntr=0.3,0.1

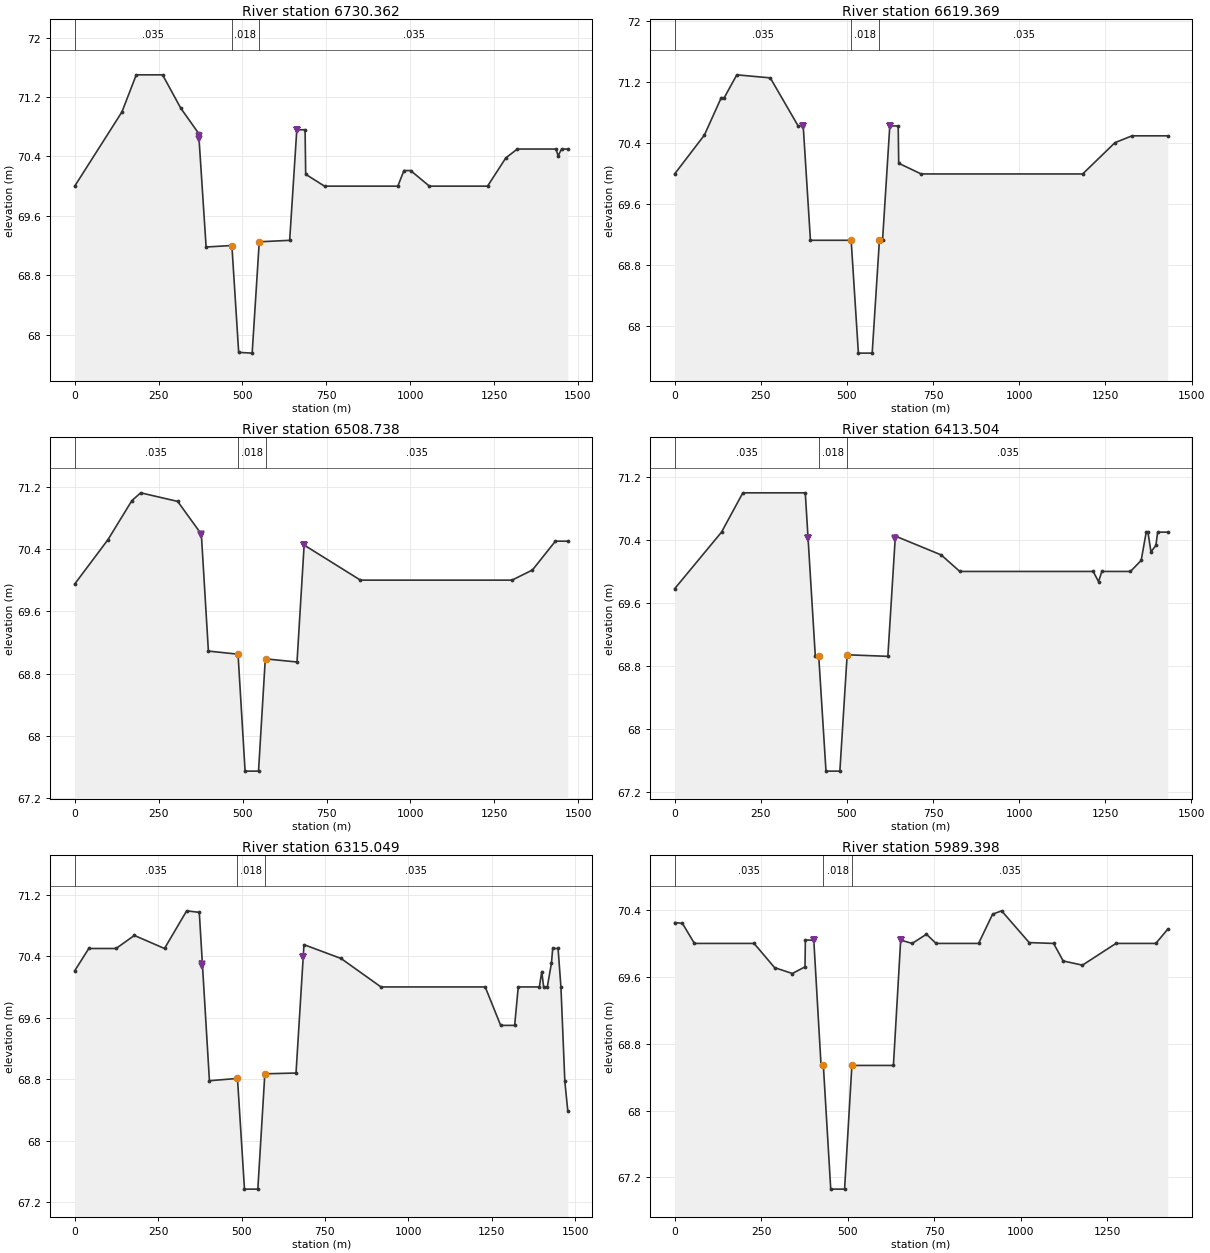
Type RM Length L Ch R = 1 ,6730.362,79.99,110.99,142
XS GIS Cut Line= 6
    1077700.1091    1572245.6639    1077774.2871    1572583.9064
    1077790.7026    1572674.0781    1077886.8148    1572731.9604
    1077901.6162    1572740.9649    1077953.2629      1573641.82
#Sta/Elev= 28
       0      70  140.82      71  183.49    71.5  261.92    71.5  316.27   71.05
  369.58   70.71  391.74   69.18  467.69    69.2  468.57    69.2  488.81   67.76
  529.02   67.75  550.13   69.25  640.79   69.27  662.05   70.76  686.75   70.76
  688.56   70.16  744.64      70  963.13      70  981.52   70.21  1001.4   70.21
 1057.27      70 1230.67      70 1285.03   70.38 1319.17    70.5 1434.49    70.5
 1441.04   70.41  1451.4    70.5 1469.79    70.5
#Mann= 3 , 0 , 0
       0    .035       0  467.69    .018       0  550.13    .035       0
Levee=-1,370.74,70.6739,-1,662.07,70.76231,	452,	451
Bank Sta=467.69,550.13
XS Rating Curve= 0 ,0
Exp/Cntr=0.3,0.1

Type RM Length L Ch R = 1 ,6619.369,75.69,110.63,145.57
XS GIS Cut Line= 4
     1077636.609    1572260.0573    1077740.8731    1572639.9945
    1077809.3023    1572885.2722    1077905.0028    1573661.2934
#Sta/Elev= 22
       0      70   86.31   70.51   135.2      71  143.89      71  180.33    71.3
  277.49   71.26  358.27   70.63     373   70.63  393.98   69.13  512.11   69.13
  533.12   67.65  573.12   67.65  594.11   69.13   603.2   69.13   624.2   70.63
   648.6   70.63  650.08   70.14  715.19      70 1183.83      70 1277.34   70.41
 1326.95    70.5 1430.53    70.5
#Mann= 3 , 0 , 0
       0    .035       0  512.11    .018       0  594.11    .035       0
Levee=-1,373.04,70.6272,-1,624.23,70.62787,	452,	451
Bank Sta=512.11,594.11
XS Rating Curve= 0 ,0
Exp/Cntr=0.3,0.1

Type RM Length L Ch R = 1 ,6508.738,137.26,95.23,53.18
XS GIS Cut Line= 6
    1077584.9622     1572271.064    1077696.0224    1572605.9842
    1077725.5092    1572696.9381    1077659.7331    1572797.3003
    1077647.6157    1572818.8584    1077849.1227    1573670.6068
#Sta/Elev= 19
       0   69.95   99.18   70.52  170.27   71.02  196.52   71.12  306.69   71.01
  377.18   70.59  398.18   69.09  486.46   69.05  507.46   67.55  547.46   67.55
  567.62   68.99  568.46   68.99   662.1   68.95  683.28   70.45     851      70
 1302.36      70 1363.21   70.13 1431.56    70.5 1468.45    70.5
#Mann= 3 , 0 , 0
       0    .035       0  486.46    .018       0  568.46    .035       0
Levee=-1,377.26,70.58814,-1,683.35,70.45036,	452,	451
Bank Sta=486.46,568.46
XS Rating Curve= 0 ,0
Exp/Cntr=0.3,0.1

Type RM Length L Ch R = 1 ,6413.504,134.85,98.46,62.09
XS GIS Cut Line= 5
    1077443.5686    1572310.0107    1077551.8597    1572656.1842
     1077611.188    1572780.7703    1077628.1423    1572851.8785
     1077822.876    1573686.6935
#Sta/Elev= 24
       0   69.78  136.03    70.5  197.96      71  379.14      71  408.15   68.93
  418.07   68.93  439.24   67.46  479.53   67.46  500.71   68.94  618.79   68.92
  640.57   70.45  773.68   70.21  827.62      70 1214.78      70 1230.26   69.87
 1239.88      70 1322.84      70 1353.98   70.14 1368.61    70.5 1373.65    70.5
 1382.39   70.25  1396.7   70.33 1401.82    70.5 1431.03    70.5
#Mann= 3 , 0 , 0
       0    .035       0  418.07    .018       0  500.71    .035       0
Levee=-1,387.18,70.42523,-1,640.1,70.4221,	452,	451
Bank Sta=418.07,500.71
XS Rating Curve= 0 ,0
Exp/Cntr=0.3,0.1

Type RM Length L Ch R = 1 ,6315.049,74.08,109.52,144.96
XS GIS Cut Line= 6
    1077313.1817    1572370.9708    1077423.2416    1572712.0683
     1077468.122    1572801.0784    1077576.7283    1572827.4692
    1077593.4289    1572833.2518    1077788.1626    1573701.9335
#Sta/Elev= 30
       0   70.21   42.21    70.5  123.98    70.5  178.76   70.67  269.18    70.5
  335.58   70.99  373.42   70.97   403.8   68.78  487.87   68.81  508.87   67.37
  548.87   67.37  569.87   68.87  663.35   68.88  687.15   70.55  798.33   70.37
  917.92      70 1230.29      70 1276.63    69.5 1318.59    69.5 1329.36      70
  1392.6      70 1399.85    70.2 1405.43      70 1416.39      70 1428.89   70.31
 1432.59    70.5 1448.72    70.5 1457.27      70 1469.02   68.77 1477.78   68.39
#Mann= 3 , 0 , 0
       0    .035       0  487.87    .018       0  569.87    .035       0
Levee=-1,382.82,70.27781,-1,684.77,70.3833,	452,	451
Bank Sta=487.87,569.87
XS Rating Curve= 0 ,0
Exp/Cntr=0.3,0.1

Type RM Length L Ch R = 1 ,5989.398,121.37,83.09,44.79
XS GIS Cut Line= 4
    1077060.3806    1572478.7799    1077233.6889    1572814.6025
    1077383.3932    1573074.5806    1077649.8734    1573773.1242
#Sta/Elev= 29
       0   70.25   22.52   70.24   57.17      70  229.63      70  289.08   69.71
  340.42   69.64  376.94   69.72  377.91   70.04  402.31   70.04  423.31   68.54
  429.95   68.54  451.32   67.06  491.32   67.06  512.44   68.54  632.51   68.54
  653.51   70.04  686.79      70  728.05   70.11  755.84      70  878.72      70
  919.33   70.35  945.31   70.39 1025.05   70.01 1095.71      70 1123.34   69.79
 1179.03   69.74 1275.93      70 1391.12      70 1425.55   70.17
#Mann= 3 , 0 , 0
       0    .035       0  429.95    .018       0  512.44    .035       0
Levee=-1,402.31,70.04148,-1,653.5,70.04148,	452,	451
Bank Sta=429.95,512.44
XS Rating Curve= 0 ,0
Exp/Cntr=0.3,0.1

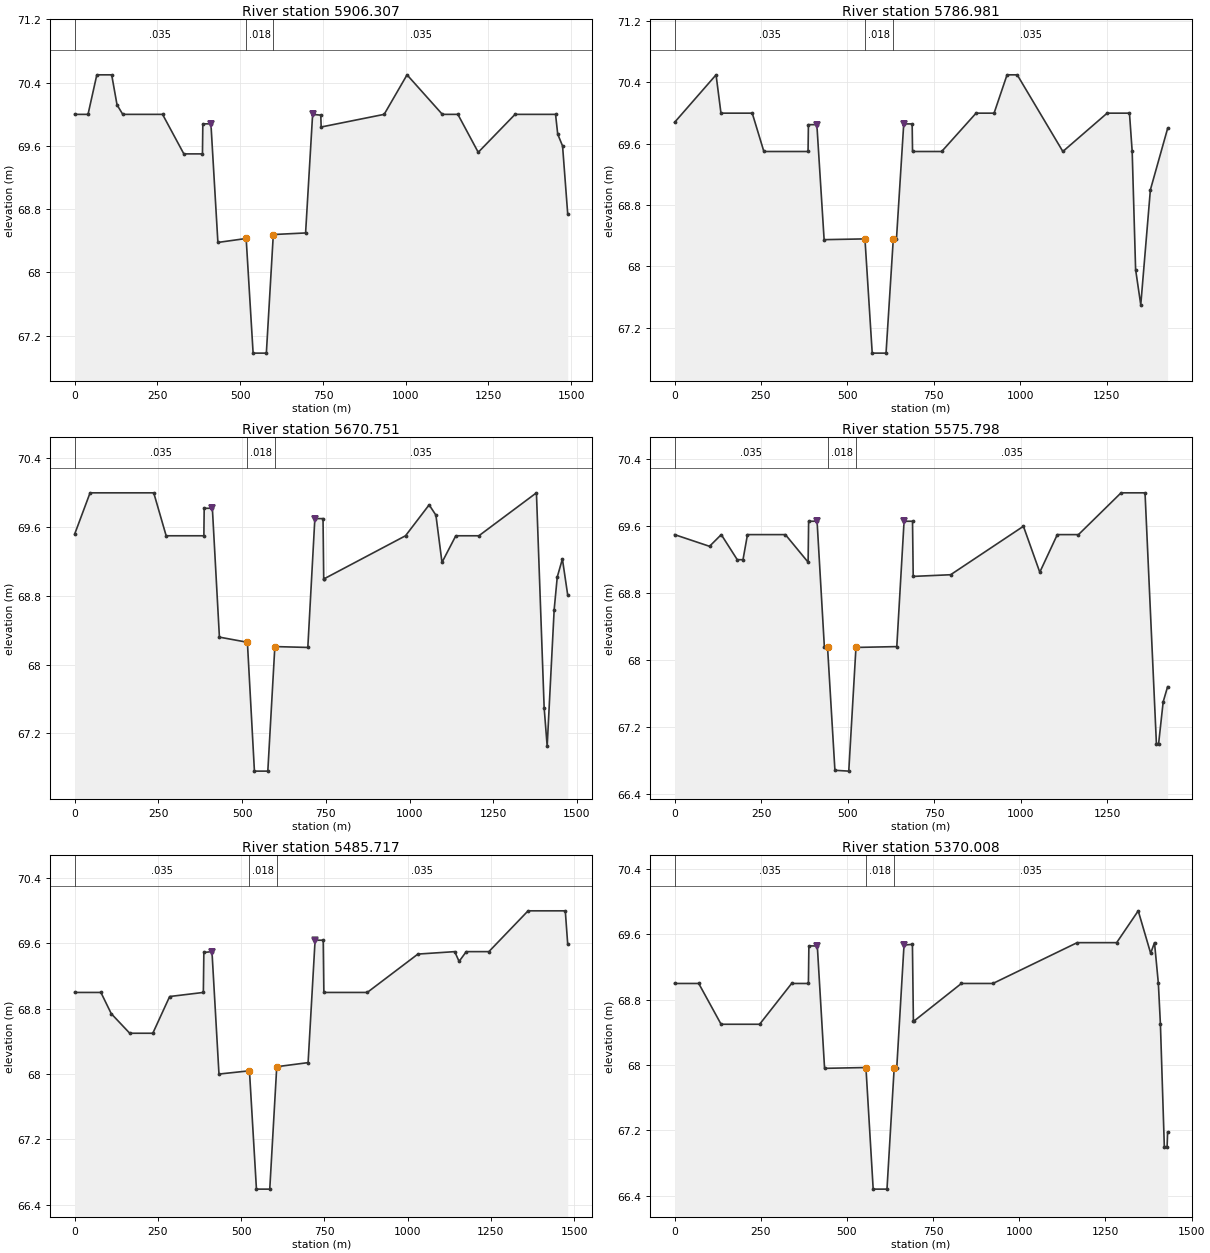
Type RM Length L Ch R = 1 ,5906.307,81.06,119.33,157.59
XS GIS Cut Line= 6
    1076939.7304    1572538.0467    1077111.7443    1572884.8224
    1077159.8641    1572957.1476    1077285.0474    1572971.6098
    1077302.7394    1572979.3726    1077621.2984    1573788.9992
#Sta/Elev= 30
       0      70   40.27      70   66.86    70.5  111.76    70.5  127.91   70.12
  145.25      70   265.4      70  329.76    69.5  385.96    69.5  387.09   69.88
  411.55   69.88  432.59   68.38  517.98   68.43  538.98   66.98  578.98   66.98
  599.98   68.48  697.51    68.5  718.74      70   743.4   69.99  744.57   69.84
  934.84      70 1003.96    70.5 1110.66      70 1157.53      70 1219.02   69.52
 1330.28      70  1452.6      70 1459.13   69.75 1473.79    69.6 1489.34   68.74
#Mann= 3 , 0 , 0
       0    .035       0  517.98    .018       0  599.98    .035       0
Levee=-1,411.54,69.87965,-1,718.73,69.99842,	452,	451
Bank Sta=517.98,599.98
XS Rating Curve= 0 ,0
Exp/Cntr=0.3,0.1

Type RM Length L Ch R = 1 ,5786.981,78.24,116.23,154.22
XS GIS Cut Line= 5
    1076899.5136    1572560.2718    1077090.7895    1572896.8889
    1077177.9757    1573035.2595     1077246.132    1573153.6204
    1077574.7316    1573815.4576
#Sta/Elev= 30
       0   69.88  120.01    70.5  134.18      70  224.66      70  258.32    69.5
  386.12    69.5  387.17   69.85  411.59   69.85   432.6   68.35  550.71   68.36
  571.73   66.87  611.73   66.87  632.72   68.36   641.9   68.36   662.9   69.86
   687.3   69.86  688.37    69.5  772.67    69.5   872.1      70  924.27      70
  961.77    70.5  991.19    70.5 1123.24    69.5 1251.27      70 1315.92      70
 1323.77    69.5 1333.68   67.96  1348.6    67.5 1376.42      69 1426.22    69.8
#Mann= 3 , 0 , 0
       0    .035       0  550.71    .018       0  632.72    .035       0
Levee=-1,411.59,69.85081,-1,662.9,69.85725,	452,	451
Bank Sta=550.71,632.72
XS Rating Curve= 0 ,0
Exp/Cntr=0.3,0.1

Type RM Length L Ch R = 1 ,5670.751,132.94,94.95,56.97
XS GIS Cut Line= 6
    1076870.9386    1572577.2051     1077067.716    1572910.1754
    1077118.5891    1572987.8393     1077072.109    1573096.5388
    1077064.6139    1573112.7229    1077505.9398    1573847.2077
#Sta/Elev= 30
       0   69.52   45.93      70  236.11      70   273.2    69.5  385.81    69.5
  386.77   69.82  411.21   69.82  432.24   68.32  515.83   68.26  536.83   66.76
  576.83   66.76  597.83   68.21   696.3    68.2  717.31    69.7  741.71    69.7
  743.77      69  745.45      69  988.08    69.5 1058.63   69.86 1078.89   69.74
 1097.03   69.19 1138.25    69.5 1207.16    69.5 1379.11      70 1402.13    67.5
 1411.17   67.05 1432.08   68.64  1441.3   69.02 1456.66   69.23 1472.54   68.81
#Mann= 3 , 0 , 0
       0    .035       0  515.83    .018       0  597.83    .035       0
Levee=-1,411.21,69.82031,-1,717.31,69.70021,	452,	451
Bank Sta=515.83,597.83
XS Rating Curve= 0 ,0
Exp/Cntr=0.3,0.1

Type RM Length L Ch R = 1 ,5575.798,128.33,90.08,51.83
XS GIS Cut Line= 4
    1076754.5217    1572643.8803    1076950.2991    1572977.7881
    1077100.0034    1573237.7662    1077475.2481    1573871.5494
#Sta/Elev= 30
       0    69.5  100.91   69.36  134.82    69.5     181    69.2  197.57    69.2
   210.5    69.5  319.97    69.5  385.58   69.17  387.07   69.66  411.47   69.66
  432.47   68.16  441.62   68.16  462.99   66.68     503   66.67  523.77   68.15
  641.67   68.16  662.67   69.66  687.07   69.66  689.05      69  797.09   69.02
 1007.31    69.6 1054.55   69.05 1105.13    69.5 1166.26    69.5 1289.24      70
 1358.44      70 1391.28      67 1397.71      67 1410.88    67.5 1423.61   67.68
#Mann= 3 , 0 , 0
       0    .035       0  441.62    .018       0  523.77    .035       0
Levee=-1,411.47,69.66111,-1,662.67,69.66111,	452,	451
Bank Sta=441.62,523.77
XS Rating Curve= 0 ,0
Exp/Cntr=0.3,0.1

Type RM Length L Ch R = 1 ,5485.717,76.24,115.71,155.18
XS GIS Cut Line= 6
    1076633.8714    1572711.6137    1076829.4693    1573046.4807
    1076877.2886    1573128.5979    1077000.4639    1573142.8945
    1077024.3972    1573148.7063    1077441.3814    1573888.4828
#Sta/Elev= 27
       0      69   78.73      69  109.78   68.74  165.32    68.5  234.63    68.5
  285.19   68.95  386.39      69  387.88   69.49  412.29    69.5  433.31      68
  524.83   68.04  545.84   66.59  585.84   66.59  606.84   68.09  700.97   68.14
  721.98   69.64  746.38   69.64   748.3      69  878.64      69 1030.75   69.47
 1141.26    69.5 1154.45   69.38 1175.95    69.5 1243.88    69.5 1361.64      70
 1473.37      70 1480.66   69.59
#Mann= 3 , 0 , 0
       0    .035       0  524.83    .018       0  606.84    .035       0
Levee=-1,412.22,69.49551,-1,721.97,69.6356,	452,	451
Bank Sta=524.83,606.84
XS Rating Curve= 0 ,0
Exp/Cntr=0.3,0.1

Type RM Length L Ch R = 1 ,5370.008,86.03,126.37,166.7
XS GIS Cut Line= 5
     1076613.763    1572720.0804    1076806.3819    1573058.7514
    1076892.0198    1573200.3694    1076955.7618    1573319.1616
    1077329.1978    1573958.3329
#Sta/Elev= 30
       0      69   70.07      69  134.95    68.5  246.67    68.5  339.58      69
  388.22      69   389.6   69.46  414.06   69.46   435.1   67.96  555.11   67.97
  576.15   66.48  616.17   66.48  637.12   67.97  644.56   67.97  665.56   69.47
  689.96   69.48  692.77   68.54  694.69   68.54  832.05      69  923.53      69
 1167.81    69.5 1282.43    69.5    1345   69.89 1381.04   69.37 1392.19    69.5
  1403.4      69 1409.36    68.5 1420.71      67 1428.75      67 1430.19   67.18
#Mann= 3 , 0 , 0
       0    .035       0  555.11    .018       0  637.12    .035       0
Levee=-1,414.06,69.46284,-1,665.53,69.47281,	452,	451
Bank Sta=555.11,637.12
XS Rating Curve= 0 ,0
Exp/Cntr=0.3,0.1

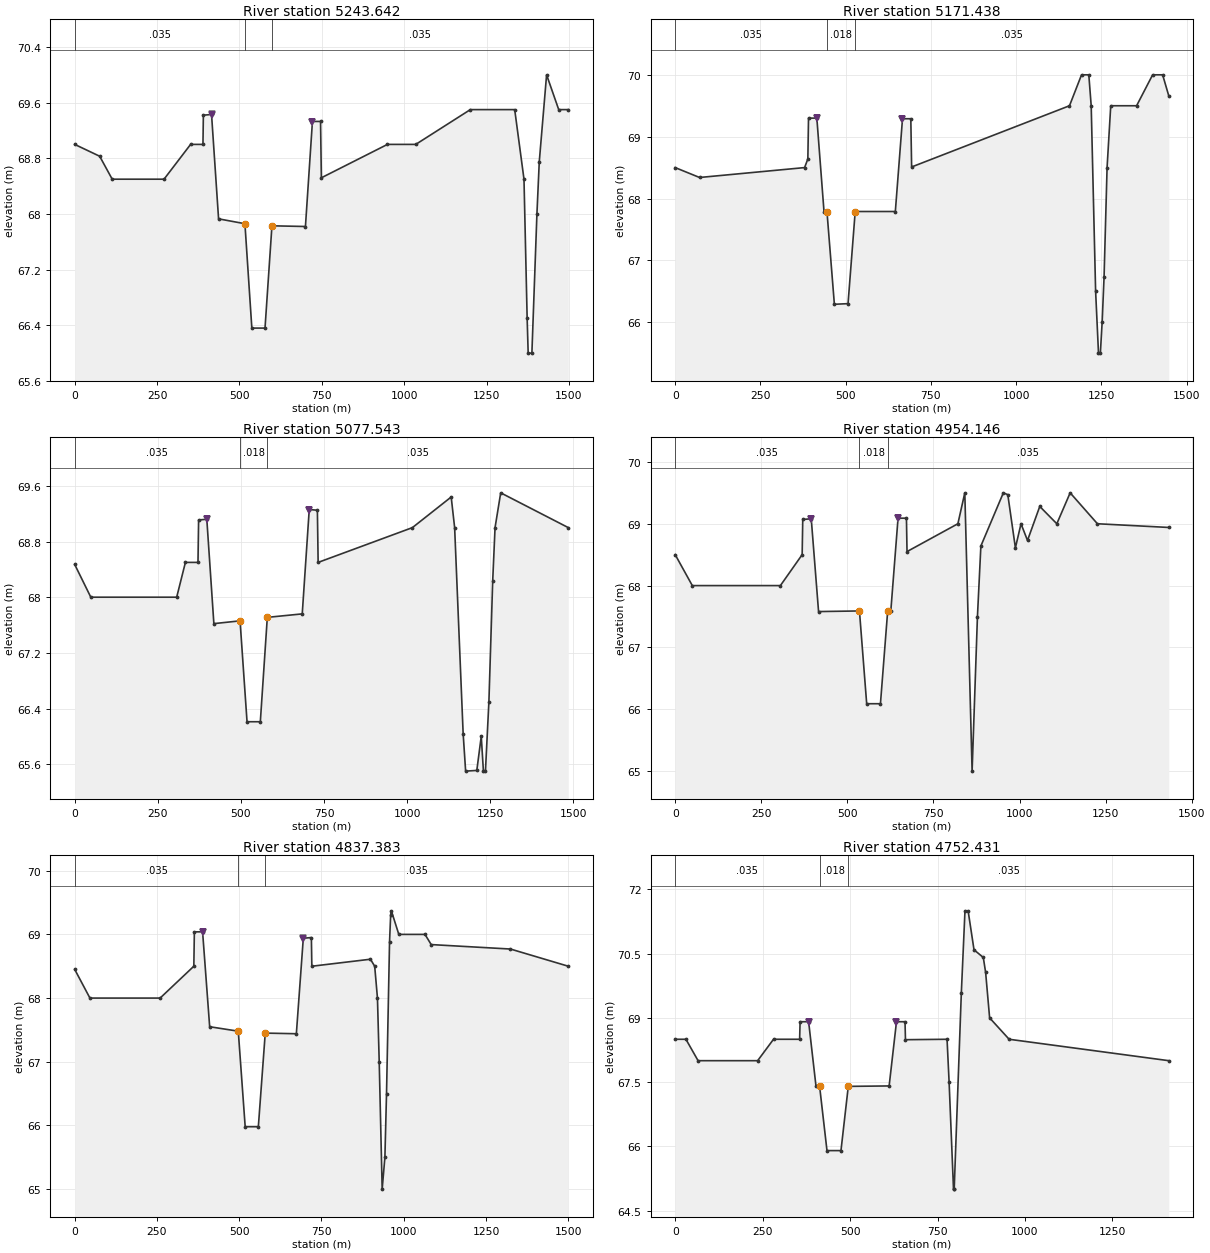
Type RM Length L Ch R = 1 ,5243.642,108.46,72.2,35.89
XS GIS Cut Line= 6
     1076564.143    1572746.4171    1076778.2474    1573072.9603
    1076830.8435    1573143.9279     1076774.338    1573249.5473
    1076768.6134    1573268.3881    1077229.6243    1574017.6896
#Sta/Elev= 30
       0      69   75.71   68.83  113.77    68.5  271.05    68.5  351.71      69
  389.21      69  390.48   69.42  415.29   69.43  436.62   67.93  516.59   67.86
  537.59   66.36  577.59   66.36  598.59   67.83  700.27   67.82  721.48   69.33
  746.11   69.33  748.58   68.52  949.16      69 1035.06      69 1200.76    69.5
  1335.4    69.5 1363.58    68.5 1373.19    66.5 1376.29      66 1387.57      66
 1402.85      68 1409.95   68.75 1432.21      70 1468.98    69.5 1498.05    69.5
#Mann= 3 , 0 , 0
       0    .035       0  516.59    .018       0  598.59    .035       0
Levee=-1,415.26,69.4268,-1,721.41,69.32336,	452,	451
Bank Sta=516.59,598.59
XS Rating Curve= 0 ,0
Exp/Cntr=0.3,0.1

Type RM Length L Ch R = 1 ,5171.438,129.85,93.89,58
XS GIS Cut Line= 4
    1076473.9728    1572787.0572     1076687.982     1573114.152
    1076802.7586    1573391.3524    1077173.7442    1574050.7097
#Sta/Elev= 30
       0    68.5   71.39   68.34  379.43    68.5     389   68.64  390.96    69.3
  415.36    69.3  436.36   67.79  445.03   67.79  466.78   66.29  506.85    66.3
  527.88   67.79  645.56   67.79  666.56   69.29  690.96   69.29  693.32   68.51
  1156.3    69.5 1191.62      70 1212.95      70 1219.94    69.5 1232.91    66.5
 1241.35    65.5 1246.81    65.5 1252.08      66 1257.68   66.73 1266.53    68.5
 1277.26    69.5 1353.11    69.5 1400.12      70 1429.45      70 1447.47   69.66
#Mann= 3 , 0 , 0
       0    .035       0  445.03    .018       0  527.88    .035       0
Levee=-1,415.32,69.29516,-1,666.51,69.28971,	452,	451
Bank Sta=445.03,527.88
XS Rating Curve= 0 ,0
Exp/Cntr=0.3,0.1

Type RM Length L Ch R = 1 ,5077.543,83.32,123.4,163.47
XS GIS Cut Line= 6
    1076382.5326    1572832.7773     1076594.623    1573246.7981
       1076703.8    1573280.6628    1076735.5933    1573293.7882
    1076769.4509    1573405.0022    1077115.3241    1574076.1098
#Sta/Elev= 30
       0   68.47   48.38      68  306.81      68  333.04    68.5  370.91    68.5
  372.77   69.11  397.46   69.12   418.7   67.62   497.5   67.66   518.5   66.21
   558.5   66.21   579.5   67.71  684.61   67.76  705.68   69.26  730.17   69.25
  732.43    68.5  1016.1      69 1132.79   69.44 1143.16      69 1168.76   66.04
 1176.23    65.5 1209.88   65.51 1223.25      66 1229.74    65.5 1235.88    65.5
 1246.28    66.5 1257.66   68.23 1264.77      69 1281.78    69.5 1485.14      69
#Mann= 3 , 0 , 0
       0    .035       0   497.5    .018       0   579.5    .035       0
Levee=-1,397.43,69.11753,-1,705.67,69.25622,	452,	451
Bank Sta=497.5,579.5
XS Rating Curve= 0 ,0
Exp/Cntr=0.3,0.1

Type RM Length L Ch R = 1 ,4954.146,77.69,116.76,155.84
XS GIS Cut Line= 5
    1076360.9426    1572840.3973    1076522.6273    1573173.6284
     1076571.763    1573278.5482     1076625.239    1573456.0351
    1076993.4038    1574123.0998
#Sta/Elev= 30
       0    68.5   49.67      68  305.51      68  368.72    68.5  370.46   69.07
  395.13   69.08  416.36   67.58  535.11   67.59  556.13   66.09   596.1   66.09
  617.11   67.59  626.21   67.59  647.21   69.09  671.61   69.09  673.27   68.55
  821.02      69  841.11    69.5  862.31      65  877.82    67.5  887.79   68.64
  953.05    69.5  966.01   69.47  988.07   68.61 1004.36      69  1023.2   68.73
 1058.81   69.28 1108.36      69  1147.1    69.5 1226.28      69 1433.53   68.94
#Mann= 3 , 0 , 0
       0    .035       0  535.11    .018       0  617.11    .035       0
Levee=-1,395.07,69.07672,-1,647.21,69.09056,	452,	451
Bank Sta=535.11,617.11
XS Rating Curve= 0 ,0
Exp/Cntr=0.3,0.1

Type RM Length L Ch R = 1 ,4837.383,120.75,84.95,49.15
XS GIS Cut Line= 6
    1076334.2725    1572855.6373    1076541.2829    1573265.8481
    1076467.9322    1573360.2821    1076457.4628    1573380.1484
    1076496.7003    1573491.0702    1076901.9637    1574158.6599
#Sta/Elev= 30
       0   68.45   46.23      68  259.58      68  362.04    68.5  363.67   69.04
  388.67   69.04  410.18   67.55  497.12   67.48  518.12   65.98  558.12   65.98
  579.12   67.45  673.65   67.44  694.77   68.94  719.31   68.95  720.72    68.5
  898.87   68.61  911.77    68.5  920.16      68   925.5      67  934.48      65
  942.79    65.5  947.72    66.5  956.91   68.88  960.34   69.31  962.43   69.37
  985.08      69 1064.59      69 1083.55   68.84 1324.44   68.77  1500.2    68.5
#Mann= 3 , 0 , 0
       0    .035       0  497.12    .018       0  579.12    .035       0
Levee=-1,388.6,69.04321,-1,694.69,68.93905,	452,	451
Bank Sta=497.12,579.12
XS Rating Curve= 0 ,0
Exp/Cntr=0.3,0.1

Type RM Length L Ch R = 1 ,4752.431,119.7,83.84,48
XS GIS Cut Line= 4
    1076284.7424    1572867.0673    1076395.3011    1573206.4879
    1076458.6237    1573499.6809    1076674.6332      1574222.16
#Sta/Elev= 30
       0    68.5   30.64    68.5   65.37      68  235.65      68  281.05    68.5
  355.73    68.5     357   68.91   381.4   68.91   402.4   67.41  412.68   67.41
  433.88    65.9  473.88    65.9   494.8    67.4  611.59   67.41  632.59   68.91
  656.99   68.91  658.24   68.49  777.15    68.5  783.01    67.5  795.58      65
  797.57      65  817.95   69.58   828.4    71.5  837.36    71.5  854.22   70.59
   880.8   70.41  887.44   70.06  898.85      69  954.63    68.5 1411.01      68
#Mann= 3 , 0 , 0
       0    .035       0  412.68    .018       0   494.8    .035       0
Levee=-1,381.33,68.90533,-1,632.53,68.90067,	452,	451
Bank Sta=412.68,494.8
XS Rating Curve= 0 ,0
Exp/Cntr=0.3,0.1